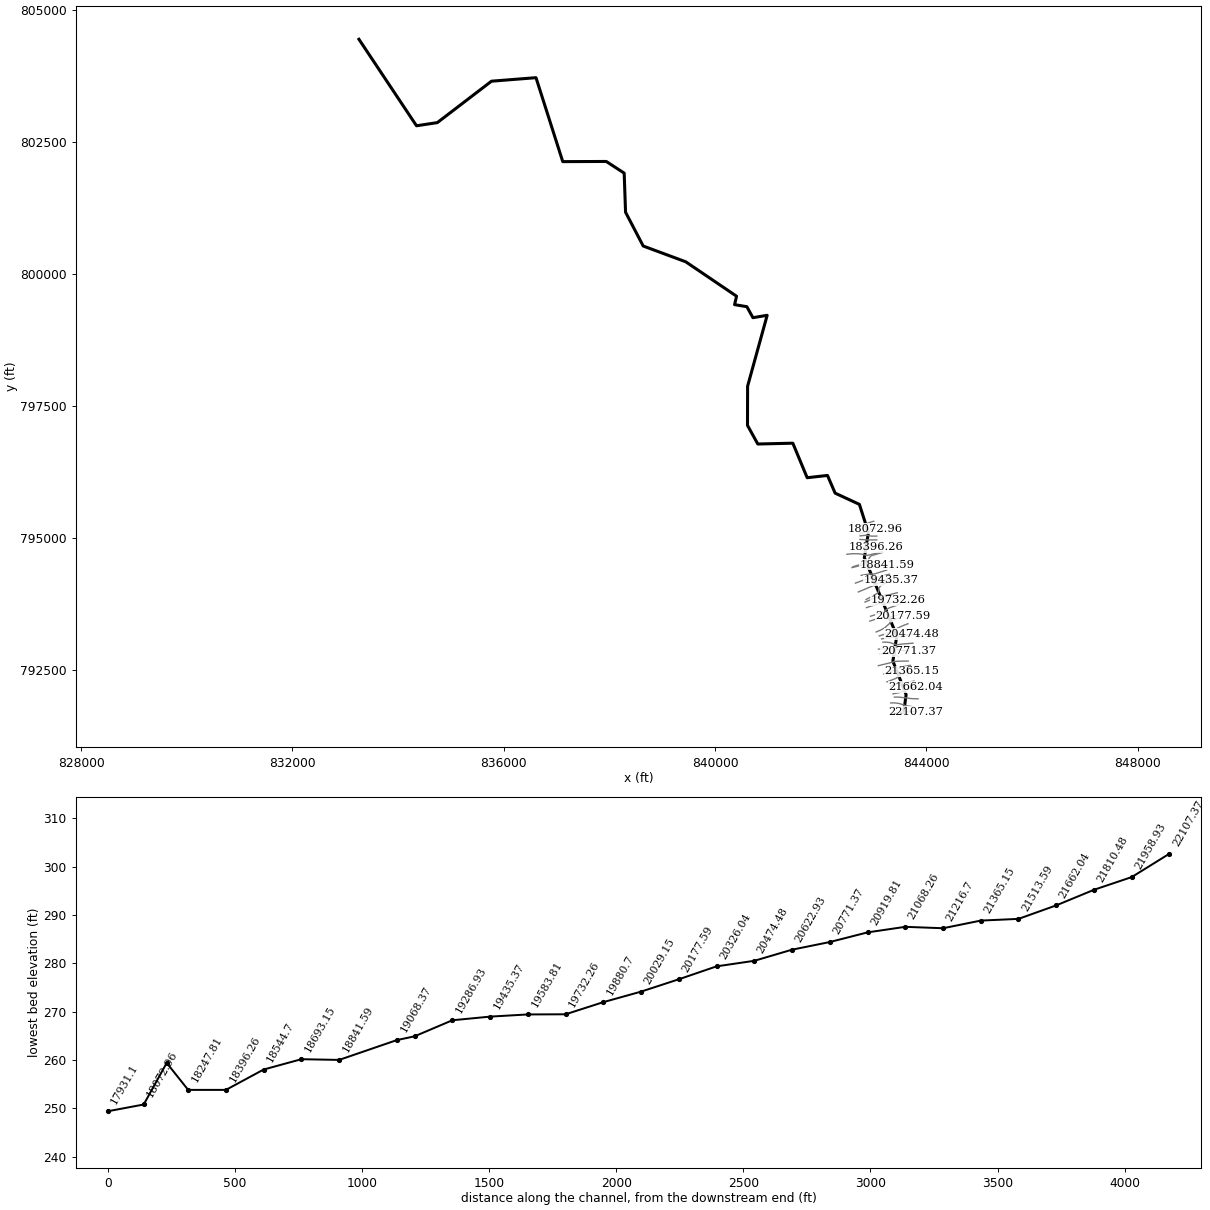
--- 17937_ras.prj (project) ---

Proj Title=17937
Current Plan=p01
Default Exp/Contr=0.3,0.1
English Units
Geom File=g01
Flow File=f01
Plan File=p01
Y Axis Title=Elevation
X Axis Title(PF)=Main Channel Distance
X Axis Title(XS)=Station
BEGIN DESCRIPTION:
RFD model 17937 exported to HEC-RAS
END DESCRIPTION:

--- 17937_ras.p01 (plan) ---

Plan Title=Plan 01
Program Version=4.10
Short Identifier=Plan 01
Geom File=g01
Flow File=f01
Subcritical Flow
Calc Critical at every XS
Secant Critical Depth

--- 17937_ras.f01 (steady flow) ---

Flow Title=Flow 01
Program Version=5.01
Number of Profiles= 6
Profile Names=10yr,25yr,50yr,100yr,100plus,500yr
River Rch & RM=17937,74,22107.37
  317.18  509.39   689.7  854.53 1247.62  1988.3
River Rch & RM=17937,74,21958.93
  327.45  526.08   712.5  882.96 1289.13 2045.85
River Rch & RM=17937,74,21810.48
   329.8  529.92  717.76  889.54 1298.73 2059.18
River Rch & RM=17937,74,21662.04
  332.15  533.76  723.02   896.1 1308.31 2072.49
River Rch & RM=17937,74,21513.59
  333.83   536.5  726.77  900.79 1315.15 2081.97
River Rch & RM=17937,74,21365.15
  389.08  626.15  849.09 1053.14 1537.59  2384.3
River Rch & RM=17937,74, 21216.7
  396.53  638.31  865.75 1073.96 1567.98 2425.48
River Rch & RM=17937,74,21068.26
  435.82  702.35  953.38 1183.39 1727.75 2639.52
River Rch & RM=17937,74,20919.81
  438.35  706.48  959.05 1190.47 1738.09 2653.31
River Rch & RM=17937,74,20771.37
  441.19  711.13  965.42 1198.43 1749.71  2668.8
River Rch & RM=17937,74,20622.93
  442.14  712.67  967.54 1201.08 1753.58 2673.95
River Rch & RM=17937,74,20474.48
  444.03  715.76  971.77 1206.38 1761.31 2684.25
River Rch & RM=17937,74,20326.04
  450.94  727.05  987.25 1225.74 1789.58 2721.87
River Rch & RM=17937,74,20177.59
   453.4   731.1  992.81 1232.71 1799.76  2735.5
River Rch & RM=17937,74,20029.15
  458.68  739.74 1004.68 1247.58 1821.46 2764.37
River Rch & RM=17937,74, 19880.7
  463.26  747.28 1015.05 1260.59 1840.46 2789.75
River Rch & RM=17937,74,19732.26
  467.53   754.3 1024.71 1272.71 1858.16 2813.36
River Rch & RM=17937,74,19583.81
  493.59  796.99 1083.36 1346.16 1965.39 2955.05
River Rch & RM=17937,74,19435.37
   496.6  801.94 1090.17 1354.71 1977.87 2971.54
River Rch & RM=17937,74,19286.93
   502.9  812.31 1104.44 1372.62 2004.02 3006.06
River Rch & RM=17937,74,19138.48
  517.31  835.98    1137 1413.45 2063.63 3084.39
River Rch & RM=17937,74,19068.37
  520.59  841.37 1144.42 1422.76 2077.22 3102.23
River Rch & RM=17937,74,18841.59
  524.16  847.24  1152.5  1432.9 2092.03 3121.64
River Rch & RM=17937,74,18693.15
  527.13  852.12 1159.22 1441.34 2104.35 3137.79
River Rch & RM=17937,74, 18544.7
  528.91  855.05 1163.25  1446.4 2111.74 3147.46
River Rch & RM=17937,74,18396.26
  530.37  857.46 1166.58 1450.58 2117.85 3155.51
River Rch & RM=17937,74,18247.81
  531.23   858.9 1168.57 1453.08  2121.5 3160.33
River Rch & RM=17937,74,18163.34
   532.1  860.33 1170.55 1455.58 2125.15 3165.16
River Rch & RM=17937,74,18072.96
  534.12  863.67 1175.17 1461.41 2133.66  3176.4
River Rch & RM=17937,74, 17931.1
  555.42  898.93 1223.92 1522.81  2223.3 3294.31
River Rch & RM=17937,74,17789.23
  558.56  904.14 1231.12 1531.88 2236.55  3311.7
River Rch & RM=17937,74,17647.37
  560.27  906.97 1235.04 1536.83 2243.77 3321.17
River Rch & RM=17937,74,17505.51
  569.68  922.56 1256.59 1563.98 2283.42 3373.05
River Rch & RM=17937,74,17221.79
  583.22  945.02 1287.69 1603.21 2340.68 3447.97
River Rch & RM=17937,74,17079.93
   584.9  947.82 1291.56 1608.09 2347.82 3457.29
River Rch & RM=17937,74,16938.07
  586.02  949.67 1294.13 1611.34 2352.55  3463.5
River Rch & RM=17937,74,16693.02
  591.86  959.38 1307.61 1628.36  2377.4 3496.01
River Rch & RM=17937,74,16447.98
  613.58  995.46 1357.59 1691.42 2469.48 3615.78
River Rch & RM=17937,74,16202.93
  619.05 1004.58 1370.25 1707.43 2492.85 3646.23
River Rch & RM=17937,74,15807.11
  626.08 1016.32 1386.58 1728.12 2523.05 3685.68
River Rch & RM=17937,74,15619.92
  627.68 1019.01 1390.33 1732.87 2529.99 3694.76
River Rch & RM=17937,74,15158.14
  632.23 1026.62 1400.93 1746.31 2549.62 3720.43
River Rch & RM=17937,74,14696.37
  777.34 1266.42 1732.21 2163.19 3158.25 4488.42
River Rch & RM=17937,74,14465.48
  778.61 1268.55 1735.18 2166.96 3163.76 4495.42
River Rch & RM=17937,74,14234.59
  891.52 1456.27 1995.56 2495.74 3643.78 5090.86
River Rch & RM=17937,74, 14003.7
  895.21 1462.47 2004.22 2506.74 3659.84 5110.85
River Rch & RM=17937,74,13772.82
   902.6 1474.88 2021.53 2528.71 3691.92 5150.73
River Rch & RM=17937,74,13541.93
  907.72 1483.48 2033.56 2544.01 3714.26 5178.58
River Rch & RM=17937,74,13311.04
  911.56 1489.98 2042.66  2555.6 3731.18 5199.75
River Rch & RM=17937,74,13080.15
  928.15 1517.86 2081.61 2605.08 3803.42 5289.38
River Rch & RM=17937,74,12849.27
  929.58 1520.28    2085  2609.4 3809.73 5297.26
River Rch & RM=17937,74, 12510.9
  933.92 1527.59 2095.23 2622.41 3828.73 5320.87
River Rch & RM=17937,74,12458.73
  934.41 1528.41 2096.37 2623.86 3830.84 5323.49
River Rch & RM=17937,74, 12106.2
 1254.37  2063.4 2841.36 3567.57 5208.65 6977.54
River Rch & RM=17937,74,11622.04
 1257.94 2069.44 2849.84 3578.37 5224.43 6996.38
River Rch & RM=17937,74,11125.35
 1265.26 2081.83 2867.24 3600.59 5256.86 7035.18
River Rch & RM=17937,74,10628.66
 1273.43 2095.69 2886.71 3625.44 5293.15 7078.58
River Rch & RM=17937,74,10380.31
 1274.75 2097.94 2889.87 3629.47 5299.02 7085.61
River Rch & RM=17937,74,10131.97
 1318.92 2172.62 2994.62    3763 5493.98 7317.19
River Rch & RM=17937,74,9883.623
 1322.85 2179.28    3004 3774.98 5511.46    7338
River Rch & RM=17937,74,9635.279
 1325.87 2184.43 3011.24 3784.24 5524.99 7354.16
River Rch & RM=17937,74, 9138.59
 1332.74 2196.14 3027.75 3805.38 5555.85 7391.06
River Rch & RM=17937,74,8602.942
 2400.16 3971.03 5492.02  6916.1 10097.512391.62
River Rch & RM=17937,74,8465.825
 2401.66  3973.6 5495.65 6920.7610104.3112399.15
River Rch & RM=17937,74,7931.888
 2456.46  4066.9 5627.19 7089.0410350.0112667.81
River Rch & RM=17937,74,6879.984
 2499.81 4141.17 5732.29 7223.9510546.9712884.29
River Rch & RM=17937,74,6786.189
 2500.73 4142.75 5734.53 7226.8210551.1612888.92
River Rch & RM=17937,74,6445.717
 2681.68 4447.24 6160.69 7768.4311341.91   13731
River Rch & RM=17937,74, 6051.88
 2688.88 4459.64 6178.29 7791.0711374.9613767.11
River Rch & RM=17937,74,5002.572
 2699.85 4478.51 6205.08 7825.55 11425.3 13822.1
River Rch & RM=17937,74,    4281
    2702 4482.22 6210.34 7832.33 11435.213832.91
River Rch & RM=17937,74,3977.595
 2701.64  4481.6 6209.46  7831.211433.5513831.11
River Rch & RM=17937,74,2198.539
 2700.57 4479.75 6206.83 7827.81 11428.6 13825.7
Boundary for River Rch & Prof#=17937,74,1
Up Type= 0
Dn Type= 2
Boundary for River Rch & Prof#=17937,74,2
Up Type= 0
Dn Type= 2
Boundary for River Rch & Prof#=17937,74,2
Up Type= 0
Dn Type= 2
Boundary for River Rch & Prof#=17937,74,2
Up Type= 0
Dn Type= 2
Boundary for River Rch & Prof#=17937,74,2
Up Type= 0
Dn Type= 2
Boundary for River Rch & Prof#=17937,74,2
Up Type= 0
Dn Type= 2

--- 17937_ras.g01 (geometry) ---

Geom Title=17937
Program Version=4.10

River Reach=17937,74
Reach XY= 30
843571.079741898791703.818462039843615.027322622792035.353811216
843365.277858378792668.565241201843438.565787377793151.436750299
842824.320543203794627.803560955842901.488365443795103.996481827
842731.262579978795636.613684644842271.974042417795848.961534735
842126.938121916796184.218154894841742.685183647796140.879119466
841471.371888043796794.488275301840808.043295921796779.082646252
840613.317323983797131.387679652840615.227150471797873.230460105
840985.452150109 799214.56274775840715.893184128799169.917397455
840601.197633236799378.103042352 840368.97114605799416.318122683
840405.959829719799576.388807961839444.307371944800227.744847768
838639.495504442800526.031654205838305.428930255801165.600998142
838279.341438174801905.667650933837940.445866615802126.518440313
837117.026184681802123.285667935836610.553212704803712.087857568
835768.105296047803645.681607591834743.365712733802861.827440903
834348.834462731802801.931607569833259.570480111804438.930095132

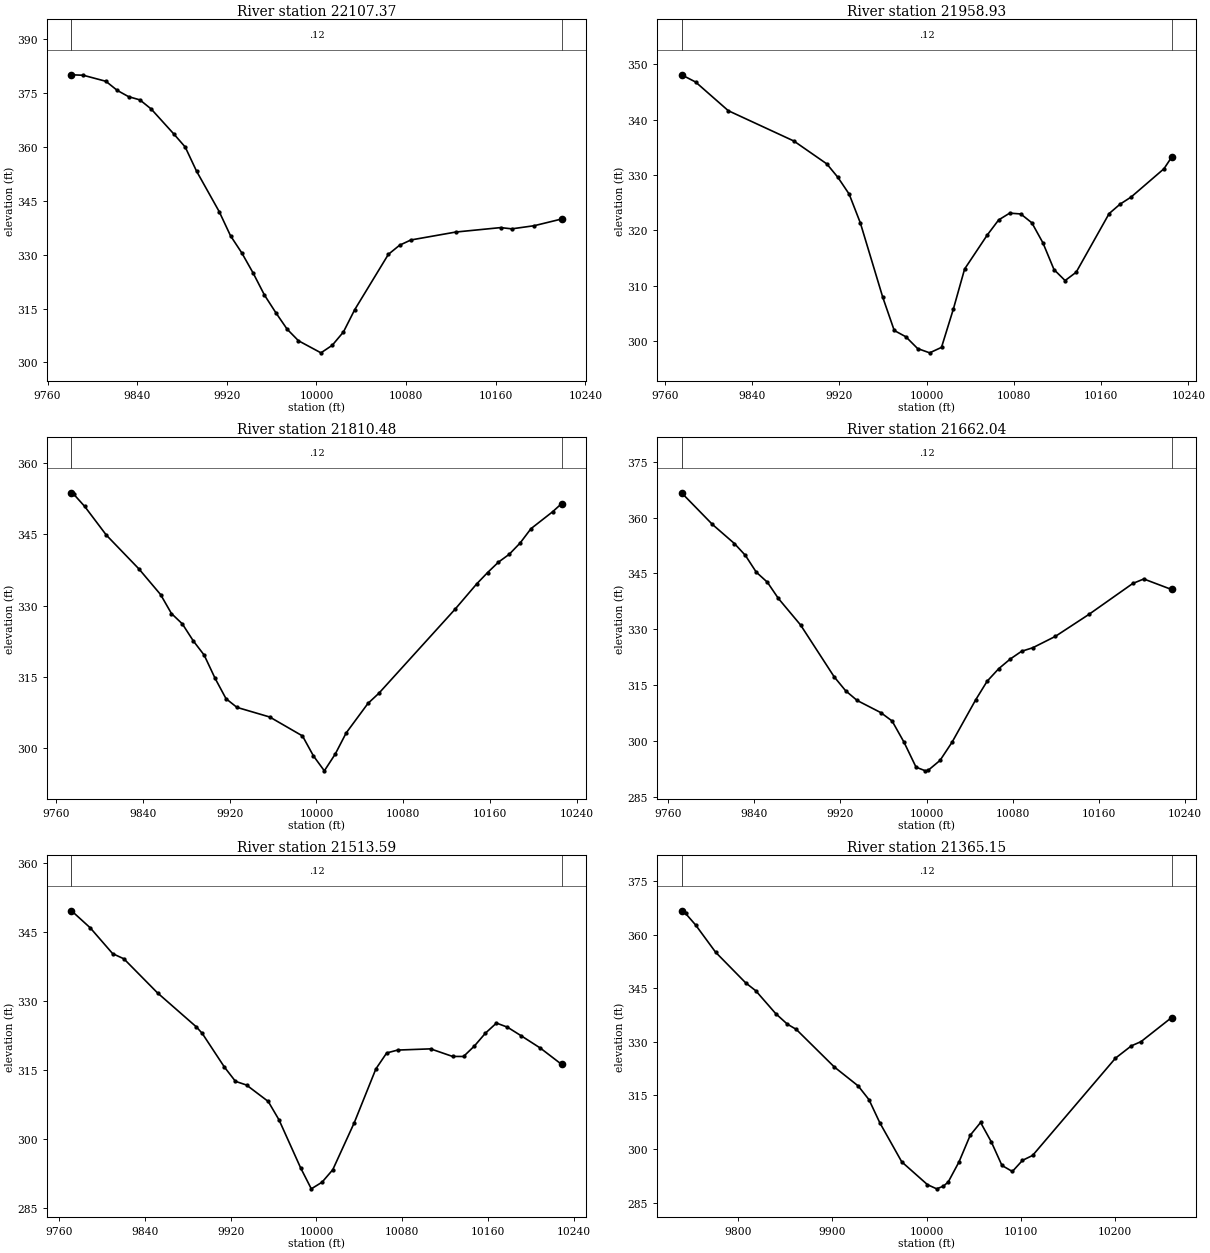
Type RM Length L Ch R = 1 ,22107.37,148.444500,148.444500,148.444500
XS GIS Cut Line= 6
843354.594870655791674.367759462843555.864752279791703.763284391
843570.032262931791704.768613508843572.029893366791704.865941006
843676.840447461791712.736890125843789.325165963791714.619776137
#Sta/Elev= 30
9781.392380.13589791.907380.00339812.119378.31859822.225375.78659832.332374.0422
9842.438373.14019852.544370.59469872.756363.62869882.862360.01129892.968353.3017
 9913.18342.02869923.286335.30079933.392330.50039943.499 324.8979953.605318.7622
9963.711313.87259973.817309.27139983.923306.052710003.98302.685210014.01304.7772
10024.03308.490310034.06314.681810064.15330.125610074.18332.6659 10084.2334.1199
10124.27336.332510164.27337.568110174.27337.222410194.28338.097510218.61339.9552
#Mann= 3 , 0 , 0
9781.392    0.12       09781.392    0.12       010218.61    0.12       0
#XS Ineff= 2 , 0
       0                               0
Bank Sta=9781.392,10218.61
Exp/Cntr=0.3,0.1

Type RM Length L Ch R = 1 ,21958.93,148.444500,148.444500,148.444500
XS GIS Cut Line= 6
843322.138518338791878.665544075843395.748138512791879.097141713
843460.715875713791872.409078253843508.124688495791861.073399657
843605.040223475791826.771418209843761.913209743791804.762558772
#Sta/Elev= 30
 9775.39348.11829788.252346.81349818.252341.62319878.335336.14479908.573332.0054
 9918.75329.56729929.032326.54969939.313321.33029959.877307.87849970.392 301.885
9981.013300.75199991.811298.619410002.86297.843410013.71298.832210024.53305.7262
10034.91313.004410055.68319.151310066.11321.875510076.23323.103910086.38322.9533
10096.54321.3536 10106.7317.724910116.86312.893910127.01310.910510137.17312.4182
10167.38323.020910177.44324.729410187.49326.004810217.66331.126510224.62333.2041
#Mann= 3 , 0 , 0
 9775.39    0.12       0 9775.39    0.12       010224.62    0.12       0
#XS Ineff= 2 , 0
       0                               0
Bank Sta=9775.39,10224.62
Exp/Cntr=0.3,0.1

Type RM Length L Ch R = 1 ,21810.48,148.444400,148.444400,148.444400
XS GIS Cut Line= 6
843392.807738513 791988.90579206843450.507980309791989.620670756
843490.726314886791987.802046962843701.610787465791962.123622881
843765.360505326791957.879838675843843.164637584791956.153904922
#Sta/Elev= 30
9773.951353.78489776.144 353.4499786.145350.91139806.146344.85989836.153337.7544
9856.173332.34369866.183328.35089876.223326.17579886.303322.60049896.383319.5928
9906.463314.69679916.542310.41119926.622308.58299956.861306.55599987.101 302.566
 9997.18298.371810007.25295.215910017.32298.749110027.38303.190610047.51309.4184
10057.58311.556910127.85329.252610147.89334.607810157.89336.9829 10167.9339.1742
 10177.9340.8381 10187.9343.2031 10197.9346.222710217.91  349.7910226.08351.4849
#Mann= 3 , 0 , 0
9773.951    0.12       09773.951    0.12       010226.08    0.12       0
#XS Ineff= 2 , 0
       0                               0
Bank Sta=9773.951,10226.08
Exp/Cntr=0.3,0.1

Type RM Length L Ch R = 1 ,21662.04,148.444500,148.444500,148.444500
XS GIS Cut Line= 6
843366.670721216792050.034627196843494.837606055 792076.34290784
843542.757155936792093.652747182843656.479134327792145.099556878
843724.292072256792164.422914746843800.242885506792180.229628416
#Sta/Elev= 30
9772.578366.63689801.215358.1503 9821.65353.01179831.804349.84499841.958 345.321
9852.204342.64489862.493338.25919883.071331.14479914.287317.21729924.919313.4815
9935.552310.88749957.523307.62439968.035305.37029979.146299.64199990.257292.9752
    9999291.9909 10001.4292.107510012.53294.794410023.66299.666310045.52  311.01
10056.26  316.0610067.01319.419510077.75322.0193 10088.2324.0837 10098.6325.0346
10119.39328.057910150.58333.962510191.43342.290310201.65343.494910227.43340.6768
#Mann= 3 , 0 , 0
9772.578    0.12       09772.578    0.12       010227.43    0.12       0
#XS Ineff= 2 , 0
       0                               0
Bank Sta=9772.578,10227.43
Exp/Cntr=0.3,0.1

Type RM Length L Ch R = 1 ,21513.59,148.444500,148.444500,148.444500
XS GIS Cut Line= 6
843318.297370661792201.043412193843474.024313173 792246.25120795
 843508.43319974792251.473381807843568.496740352792253.951474801
 843605.68252331792258.418003254843764.269760199792292.997836508
#Sta/Elev= 30
 9771.56349.68819789.031345.98259809.951340.36249820.411339.24089851.791331.8206
9888.074324.41089893.493323.00849914.128315.69189924.446312.58529934.744311.7814
9954.973308.21289965.088304.18919985.145293.78979995.156289.197610005.16290.6388
10015.17293.352310035.23303.594410055.37315.289510065.44318.754710075.67319.3859
10106.37319.650210126.84318.004210137.08317.990610147.31320.290610157.55323.0748
10167.78325.260610178.02324.3705 10190.9322.486810208.72319.817210228.44316.2927
#Mann= 3 , 0 , 0
 9771.56    0.12       0 9771.56    0.12       010228.44    0.12       0
#XS Ineff= 2 , 0
       0                10085.88       0
Bank Sta=9771.56,10228.44
Exp/Cntr=0.3,0.1

Type RM Length L Ch R = 1 ,21365.15,148.444400,148.444400,148.444400
XS GIS Cut Line= 6
843251.001913322792275.859817825843418.820745494792342.294041546
843514.377138187792404.544839671843561.274809742792428.561637259
843633.265004283792454.965308814843726.562559985792479.296199969
#Sta/Elev= 30
9739.684366.75459743.944366.01669754.597362.79279775.904355.13739807.864346.5526
9818.517344.35419839.824337.91989852.126334.98269861.513333.53679902.047322.9789
9927.355317.67969938.847313.82669950.339307.35339973.678296.3958   10001290.0083
10010.77288.843810017.89289.5937   10023290.754710034.47296.3873 10046.4303.8631
10057.41307.436410068.87301.962210080.11295.395110091.17293.706810101.93296.8219
10112.69298.205710200.73325.462310217.59328.906210227.87330.090810260.31336.8264
#Mann= 3 , 0 , 0
9739.684    0.12       09739.684    0.12       010260.31    0.12       0
#XS Ineff= 2 , 0
       0                10060.77       0
Bank Sta=9739.684,10260.31
Exp/Cntr=0.3,0.1

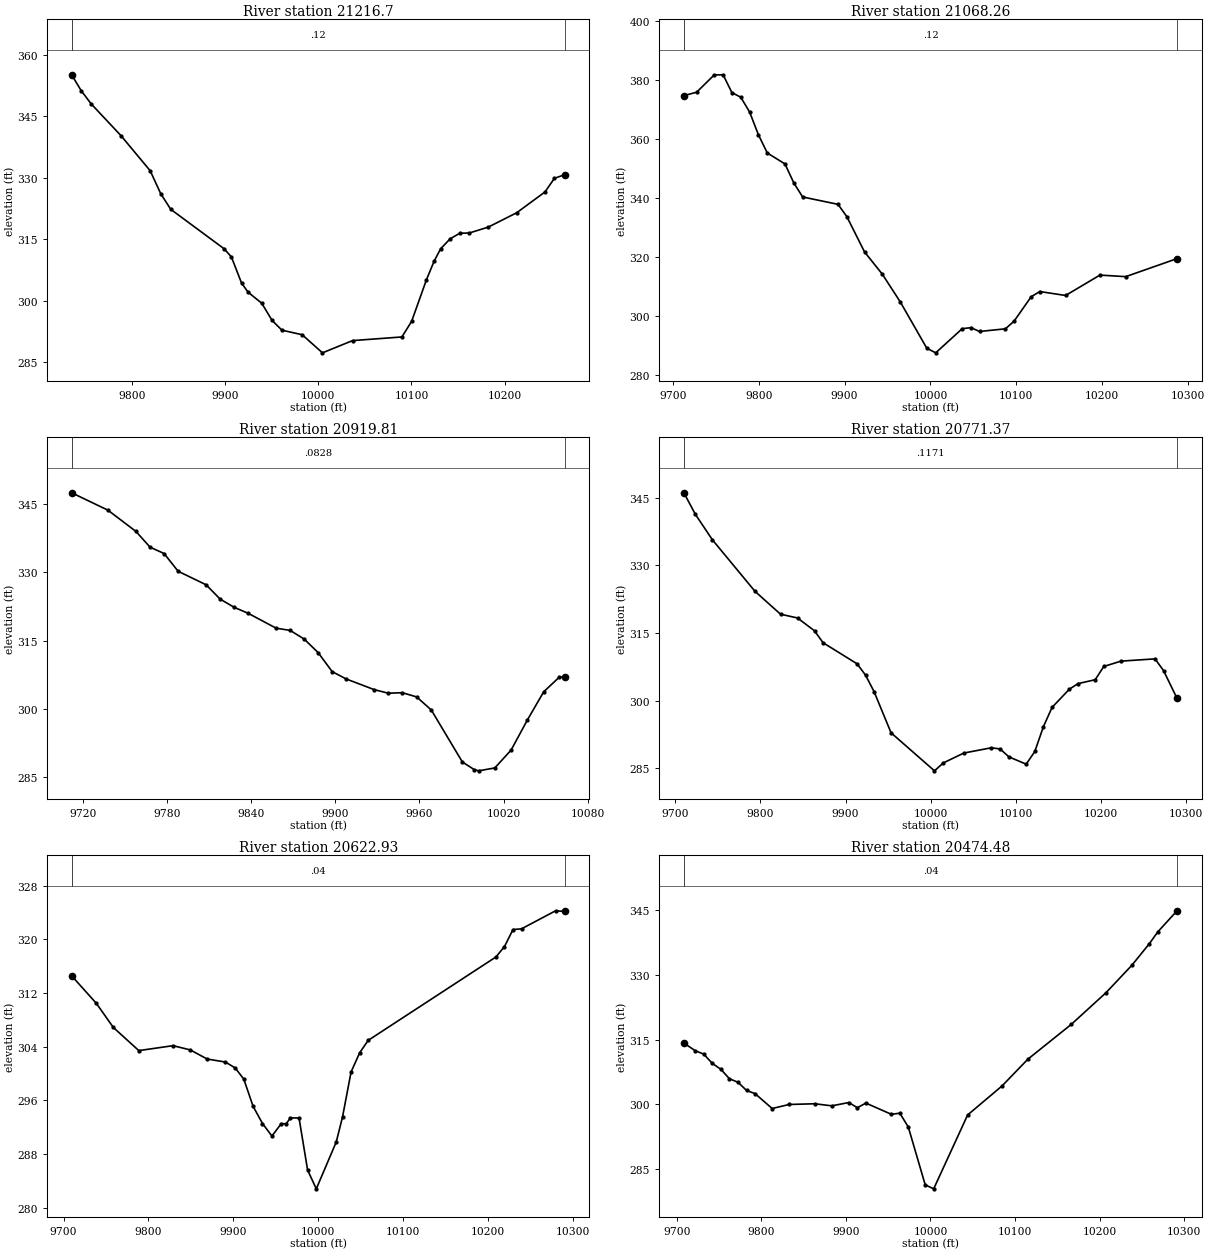
Type RM Length L Ch R = 1 , 21216.7,148.444500,148.444500,148.444500
XS GIS Cut Line= 6
843195.406925116792425.455719633843293.995209244792462.351039805
843456.026821718792530.967450255843508.427769049792550.532354381
843587.276152731792572.067356777 843696.03634064792590.912438288
#Sta/Elev= 30
9735.327355.0589 9745.57351.18759756.247347.97379788.279  340.22 9819.62331.6639
9830.989326.04649841.683322.25699898.929 312.6449906.791310.65169917.642304.3052
9924.685302.05169939.345299.36029950.442295.17049961.047292.7834 9982.75291.6776
10004.53287.260710036.81290.2445 10089.8291.133710100.24294.934210116.14 305.082
10124.29309.566210131.34 312.62610141.63315.074610151.92316.423210162.13316.4795
 10182.5317.916410213.01321.418210243.37326.490510253.49329.807410264.66330.7129
#Mann= 3 , 0 , 0
9735.327    0.12       09735.327    0.12       010264.66    0.12       0
#XS Ineff= 2 , 0
       0                10042.51       0
Bank Sta=9735.327,10264.66
Exp/Cntr=0.3,0.1

Type RM Length L Ch R = 1 ,21068.26,148.444500,148.444500,148.444500
XS GIS Cut Line= 6
843090.639890966792584.098739485843302.489376145792635.680671368
843390.165878903792659.414193009843413.496158575792663.986906615
843464.280058551792668.143114822843654.762975377792671.587918959
#Sta/Elev= 30
9712.925 374.7819727.704375.92069748.289381.79849758.581381.84569768.873375.7925
9779.165 374.2349789.457369.22099799.749361.46989810.042355.32369830.626351.6217
9840.918345.1667 9851.21 340.4099892.379337.90999902.671333.72299923.255321.7656
9943.926314.23159964.649304.91669995.734289.111710006.09287.553710036.91295.7407
10047.08296.097410057.11294.795210087.21 295.70110097.24 298.26710117.25306.5826
10127.25308.340710157.25307.002810197.26313.917810227.26313.390210287.04 319.504
#Mann= 3 , 0 , 0
9712.925    0.12       09712.925    0.12       010287.04    0.12       0
#XS Ineff= 2 , 0
       0                               0
Bank Sta=9712.925,10287.04
Exp/Cntr=0.3,0.1

Type RM Length L Ch R = 1 ,20919.81,148.444400,148.444400,148.444400
XS GIS Cut Line= 6
843129.143082276    792805.18502843249.519177159792811.867432441
843317.992412831792811.813097655843362.387745256792808.969584768
843392.314811722792801.012004946843468.562298959792757.977865681
#Sta/Elev= 30
9711.563347.44939737.492343.62979757.547338.94849767.574335.50269777.594334.1153
  9787.6330.22149807.613327.24589817.619324.10889827.625322.30579837.628320.9901
9857.628 317.7229867.628317.23399877.628315.33419887.628312.35019897.628308.1868
9907.643306.57329927.684304.22829937.704303.44759947.771 303.5559957.968302.6321
9968.399299.77359990.628288.3402    9999286.693910002.14286.402610013.79287.0392
10025.43290.963410037.07297.581610048.71 303.75610059.92306.992710063.79306.9752
#Mann= 3 , 0 , 0
9711.563  0.0828       09711.563  0.0828       010063.79  0.0828       0
#XS Ineff= 2 , 0
       0                               0
Bank Sta=9711.563,10063.79
Exp/Cntr=0.3,0.1

Type RM Length L Ch R = 1 ,20771.37,148.444500,148.444500,148.444500
XS GIS Cut Line= 6
 843091.56439061 792897.68780739843337.520876628792903.550420343
843392.775839747792914.576675691843427.453324641  792894.1830493
843463.652157903792883.778457056843660.821936934792858.007419224
#Sta/Elev= 30
9709.944346.05819723.427341.29069743.497 335.629 9793.56324.21069823.576 319.137
9843.576318.29969863.576315.44769873.576312.81779913.576308.14139923.576305.6257
9933.576301.97439953.576292.836510004.62284.406410014.98286.159710039.15288.3513
 10071.4289.5174 10081.8289.258810092.17287.495810112.47285.886310122.61288.7005
10132.76294.229510142.91298.4839 10163.2302.505310173.35303.739210193.64304.6156
 10203.7307.549110223.82308.726610263.97309.2339   10274306.623910289.85300.4639
#Mann= 3 , 0 , 0
9709.944  0.1171       09709.944  0.1171       010289.85  0.1171       0
#XS Ineff= 2 , 0
       0                 10039.2       0
Bank Sta=9709.944,10289.85
Exp/Cntr=0.3,0.1

Type RM Length L Ch R = 1 ,20622.93,148.444400,148.444400,148.444400
XS GIS Cut Line= 6
 843175.89223836793028.520226181843245.718823303793029.230972884
843311.906889921793021.171465087843437.583246071792976.378651935
843513.694161899792990.457641998843745.839674026 793009.81860462
#Sta/Elev= 30
9709.556314.54949738.665310.45249758.666306.86449788.696303.41249828.997304.1491
9849.322303.51499869.217302.1614 9890.83301.70519902.244 300.8299912.387299.1703
9923.322295.12059934.428292.55529945.533290.69059956.639292.54659962.275292.5045
9967.295293.38689977.488 293.3829987.576285.61759997.818282.826110021.34289.8138
 10028.7293.5253 10038.8300.2311 10048.9303.087810058.99304.942210209.51317.3615
10219.55318.913610229.58321.442910239.62321.548310279.76324.237310290.63324.1382
#Mann= 3 , 0 , 0
9709.556    0.04       09709.556    0.04       010290.63    0.04       0
#XS Ineff= 2 , 0
       0                               0
Bank Sta=9709.556,10290.63
Exp/Cntr=0.3,0.1

Type RM Length L Ch R = 1 ,20474.48,148.444500,148.444500,148.444500
XS GIS Cut Line= 6
843151.780361038793090.813965166843238.852530302793104.663898516
  843361.4729399793120.142370832843462.853636409793126.646367048
843494.344403278793130.480512249843727.032130989793181.941039049
#Sta/Elev= 30
9708.275314.17929721.661312.42029731.786311.62649741.912309.48549752.038308.1224
9762.163305.94249772.289 305.1249782.415303.24569792.541302.50269812.717299.0711
9832.876299.99949863.114300.16639883.273 299.6849903.431300.45139913.511 299.251
9923.579300.3214 9953.72297.73459963.767297.98689973.779294.79489993.789281.4495
 10003.8280.525110043.98 297.58410084.64304.272910115.26310.460710166.55 318.482
10207.58325.786310238.35332.156710258.87 337.09910269.12  339.8910291.72344.7155
#Mann= 3 , 0 , 0
9708.275    0.04       09708.275    0.04       010291.72    0.04       0
#XS Ineff= 2 , 0
       0                               0
Bank Sta=9708.275,10291.72
Exp/Cntr=0.3,0.1

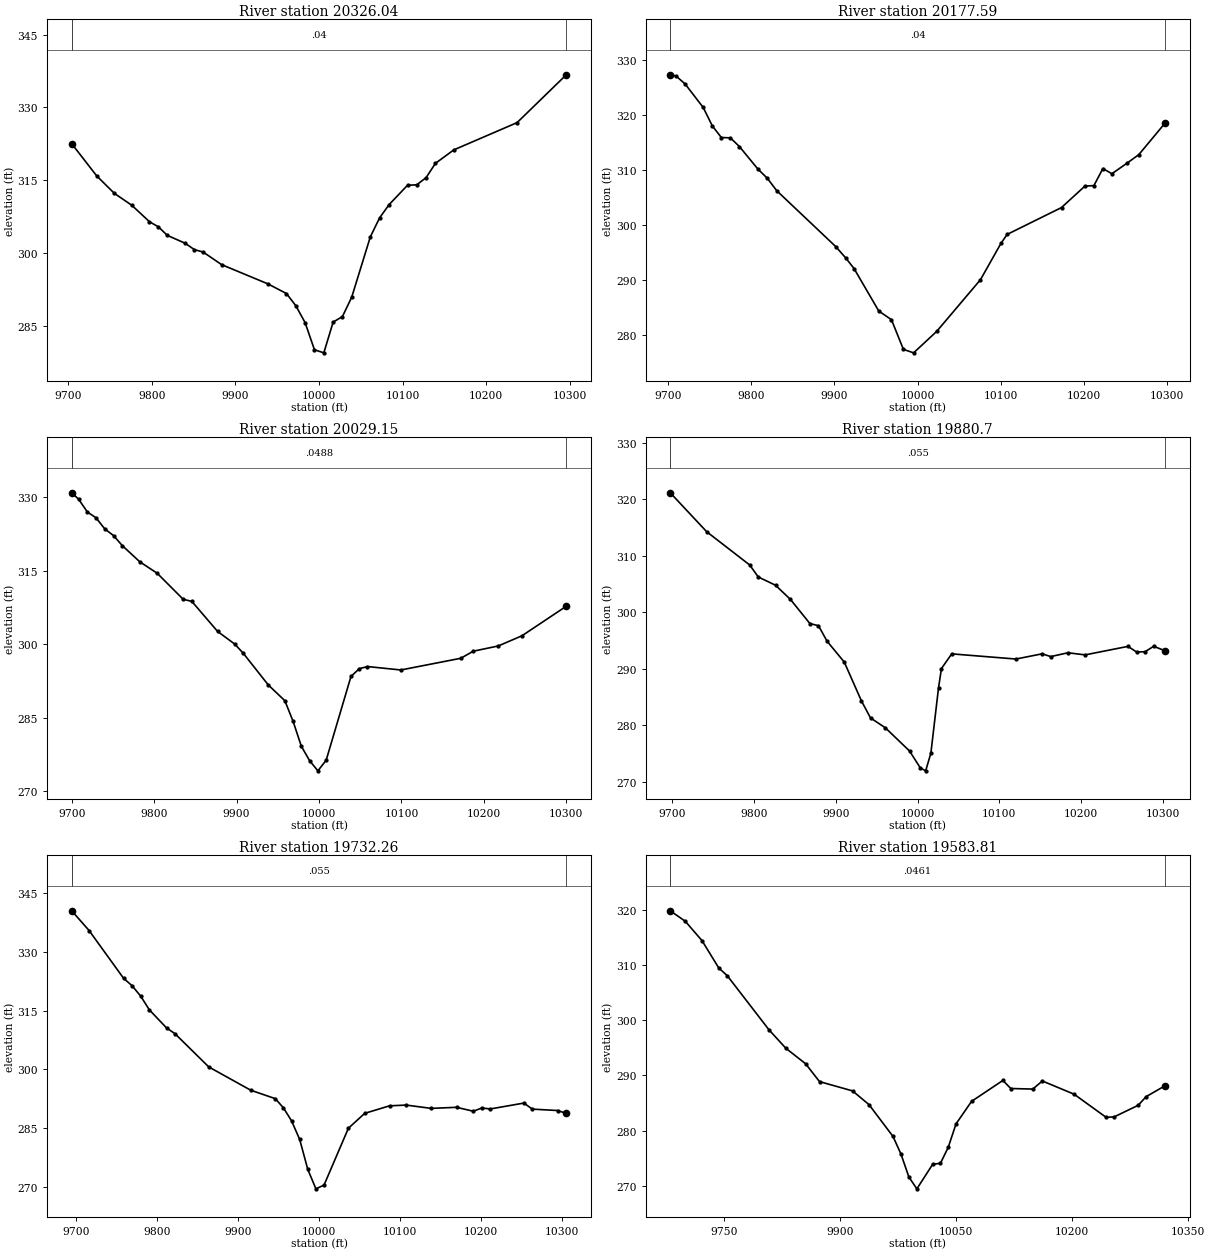
Type RM Length L Ch R = 1 ,20326.04,148.444500,148.444500,148.444500
XS GIS Cut Line= 6
843106.503135808793147.180904764843192.073087622793174.442382201
843252.728108969793197.591488834843515.225359506 793324.06943557
843571.834181213 793348.21008548843650.080476941793377.601872829
#Sta/Elev= 30
 9704.37322.51729734.278315.86969755.268312.28649776.259309.8099 9797.31306.4243
9808.014305.36499818.717303.60239840.124301.97349850.828300.68659861.594300.1552
 9883.55 297.5749938.747293.61619961.068291.61269972.229289.10839983.389285.6137
 9994.55280.018610005.78279.3774 10016.9285.721110028.01286.855610039.13290.8639
10061.35303.289110072.47307.228310083.88309.961910105.81313.942710116.92314.0398
10128.03315.515910139.15318.457110161.14321.2396 10236.8326.861910295.64 336.733
#Mann= 3 , 0 , 0
 9704.37    0.04       0 9704.37    0.04       010295.64    0.04       0
#XS Ineff= 2 , 0
       0                               0
Bank Sta=9704.37,10295.64
Exp/Cntr=0.3,0.1

Type RM Length L Ch R = 1 ,20177.59,148.444400,148.444400,148.444400
XS GIS Cut Line= 6
843048.546103759 793221.54793419843132.534002289793257.217626727
843210.122158923 793301.00512264843338.156746702793414.719121655
843379.694659217793444.183975719843553.886518864793522.308443761
#Sta/Elev= 30
9703.001327.33219710.013   327.19720.877325.65649742.606321.37559753.471318.0395
9764.335315.9107  9775.2315.84729786.064314.26859808.328310.15329819.623308.4829
9830.917306.21989901.654296.06419914.023293.93239923.704292.05929953.426284.3159
 9968.67282.73619983.014277.33169995.273276.704410022.96280.604910075.57290.0249
10100.09296.615110107.53298.262810172.87303.157610200.97307.061510211.77307.1525
10222.57310.263510233.37309.315410251.12311.190910265.77312.799110296.96318.4876
#Mann= 3 , 0 , 0
9703.001    0.04       09703.001    0.04       010296.96    0.04       0
#XS Ineff= 2 , 0
       0                               0
Bank Sta=9703.001,10296.96
Exp/Cntr=0.3,0.1

Type RM Length L Ch R = 1 ,20029.15,148.444500,148.444500,148.444500
XS GIS Cut Line= 6
842927.119531779793427.077236706843114.403699719793488.632105909
843172.251058358793497.790355132843254.033184265793493.399961656
843309.131575191793499.158457315843505.793779678793562.316662312
#Sta/Elev= 30
9700.003330.93619708.358329.62769718.961327.02619729.563325.80739740.166323.5501
9750.768322.18689761.371320.14619782.576316.84429803.781314.4888  9835.3309.1765
9845.722308.76119876.988302.62069897.818300.02929908.015298.18579938.481291.6882
9958.583288.47279968.583284.24899978.583279.1705 9988.61276.22239998.652274.1503
 10008.7276.324810038.78293.4212 10048.8 295.00610058.81295.448910099.29294.7483
   10172297.138210187.15298.583410217.39299.650110246.17 301.72810299.99307.7677
#Mann= 3 , 0 , 0
9700.003  0.0488       09700.003  0.0488       010299.99  0.0488       0
#XS Ineff= 2 , 0
       0                               0
Bank Sta=9700.003,10299.99
Exp/Cntr=0.3,0.1

Type RM Length L Ch R = 1 , 19880.7,148.444500,148.444500,148.444500
XS GIS Cut Line= 6
842942.560451196793519.411474824843167.285510747793592.699220953
843198.165949534793608.651598245843251.527650231793652.631121378
843294.624096351793677.252767419843498.044578766793746.992370847
#Sta/Elev= 30
9697.459321.17779742.098314.2796 9794.69308.39789805.208306.27419826.245304.8179
9844.494302.31159868.318298.03859878.837 297.6539889.355294.90849910.392291.2172
9931.428 284.3349942.515281.33089960.633 279.5929990.344275.468410003.42272.4911
10009.97271.972610016.36275.103610025.72286.6768 10029.3290.077210041.86292.6718
10120.41 291.75710152.43292.678310163.06  292.1910184.08292.867110205.05292.4925
10257.48293.995510267.96293.008910278.45293.048210288.93294.010510302.61293.2379
#Mann= 3 , 0 , 0
9697.459   0.055       09697.459   0.055       010302.61   0.055       0
#XS Ineff= 2 , 0
       0                               0
Bank Sta=9697.459,10302.61
Exp/Cntr=0.3,0.1

Type RM Length L Ch R = 1 ,19732.26,148.444400,148.444400,148.444400
XS GIS Cut Line= 6
842864.816446725793682.403140374843053.766078647 793744.76891932
843117.314162657793755.355130334843187.426317885793753.480880652
843224.764592553793757.470199219843455.336158648793819.547628963
#Sta/Elev= 30
9694.947340.56349716.376335.51839758.845323.32039769.462321.3838 9780.08318.7241
9790.697 315.2399811.931310.61229822.392309.1185 9864.05300.62939915.694294.6896
9946.078292.52269956.154290.16169966.173286.83169976.175282.08199986.185274.4193
9996.203269.460710006.22270.429110036.28284.9631 10056.4288.7647   10087 290.687
10107.54290.879610138.49290.032710169.66290.308710190.43289.300710200.82290.1385
10211.21289.886610252.76291.393510263.14289.844910294.31289.486610305.04288.7482
#Mann= 3 , 0 , 0
9694.947   0.055       09694.947   0.055       010305.04   0.055       0
#XS Ineff= 2 , 0
       0                               0
Bank Sta=9694.947,10305.04
Exp/Cntr=0.3,0.1

Type RM Length L Ch R = 1 ,19583.81,148.444500,148.444500,148.444500
XS GIS Cut Line= 6
842837.142629133793787.075993764843024.414375518793865.952071916
843082.440145634793886.657860585843147.187703012793902.252193279
843282.992486738793922.368661685843448.287810129793965.042851553
#Sta/Elev= 30
9680.253319.8503 9699.63317.95399721.332314.43629743.033309.47259753.884308.0956
9808.138298.2296 9829.84294.90759855.243292.11419873.243288.87619915.933287.1898
9937.168 284.7129968.281278.93029978.571275.7375 9988.86271.55379999.151269.4298
10019.54273.875310029.61274.064510039.68276.949610049.76281.2098 10069.9285.2983
10110.39289.091110120.55287.622910149.02 287.51910161.37288.9888 10202.5286.5838
10243.78282.401110254.14282.472610285.25284.572710295.61286.149910319.75288.1013
#Mann= 3 , 0 , 0
9680.253  0.0461       09680.253  0.0461       010319.75  0.0461       0
#XS Ineff= 2 , 0
       0                               0
Bank Sta=9680.253,10319.75
Exp/Cntr=0.3,0.1

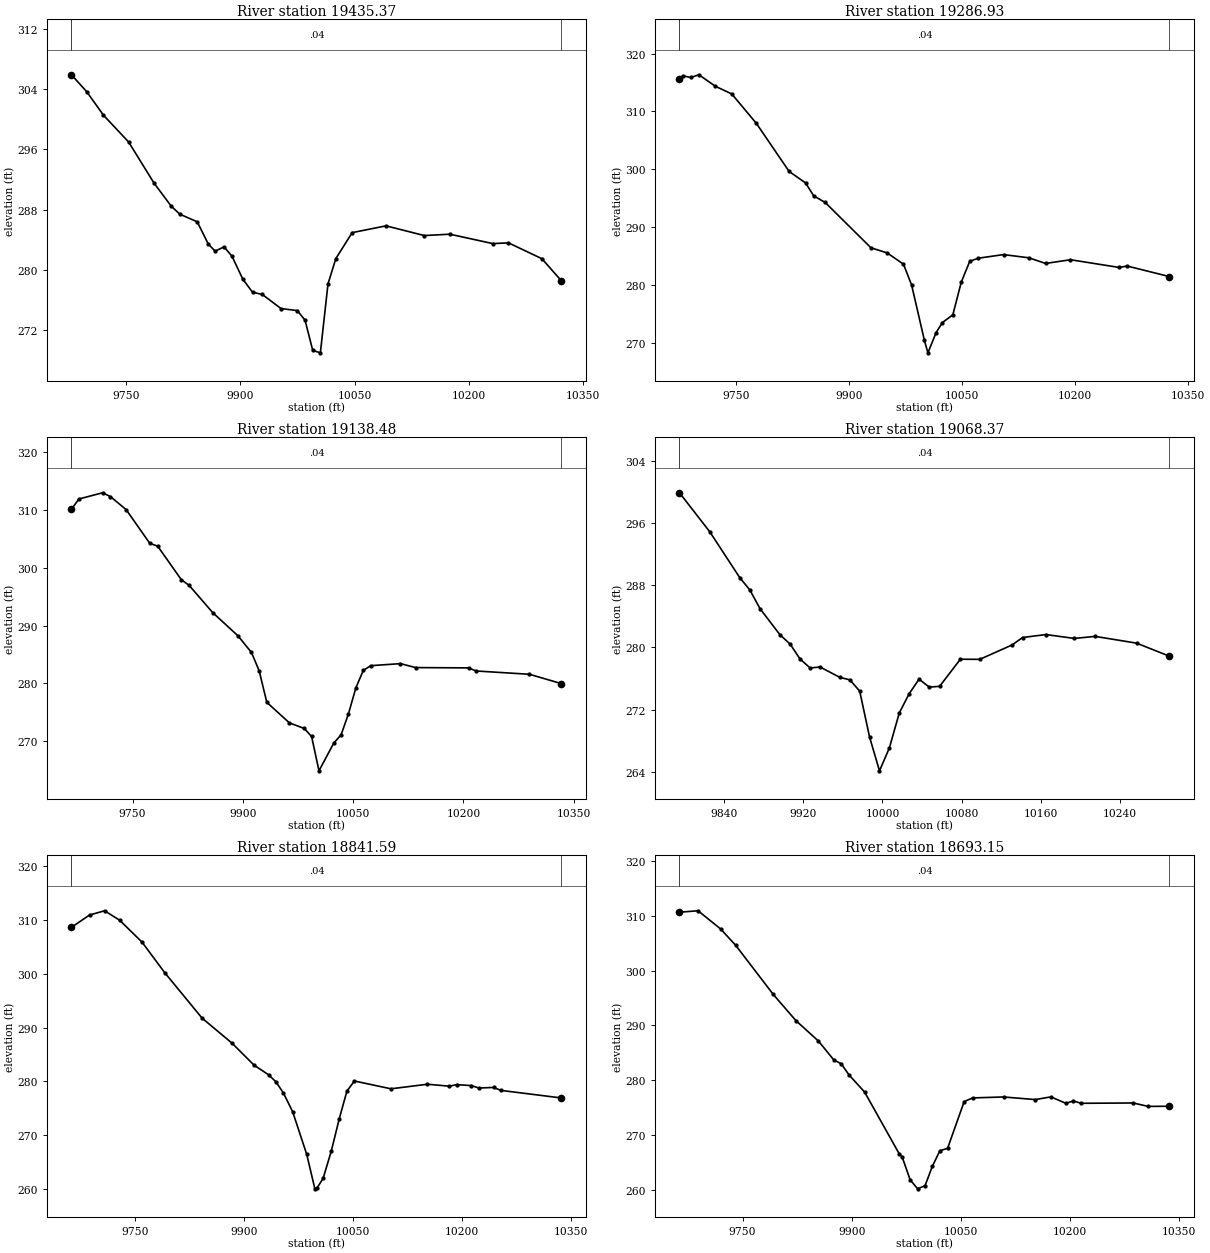
Type RM Length L Ch R = 1 ,19435.37,148.444500,148.444500,148.444500
XS GIS Cut Line= 6
842856.814128124793835.207662287843075.056329881793955.966879984
843096.658675577793988.639887413843102.469719665794058.443643876
843147.210202367794109.774484893843339.037317787794200.823698526
#Sta/Elev= 30
9678.758305.8821 9698.74303.63659720.714300.52119753.676 296.9669787.154291.4889
9809.598288.4467 9820.82287.38079843.729286.36739858.117283.42399867.158282.4736
9878.873283.04679889.376281.78099903.465278.75869916.234277.01789929.003276.7311
9953.526274.85499975.022274.58519985.096273.30539995.151269.304110005.17 268.979
10015.17 278.12410025.47 281.49310046.91284.933110091.29285.8324 10141.5284.5443
10174.93284.724810231.29283.478710251.85283.576610295.64281.475110321.23278.5495
#Mann= 3 , 0 , 0
9678.758    0.04       09678.758    0.04       010321.23    0.04       0
#XS Ineff= 2 , 0
       0                               0
Bank Sta=9678.758,10321.23
Exp/Cntr=0.3,0.1

Type RM Length L Ch R = 1 ,19286.93,148.444400,148.444400,148.444400
XS GIS Cut Line= 6
842711.233213331793978.865053909843032.725876308794114.425310707
843135.455312543794166.697889701843186.581966484794190.499293994
843236.340128933794210.614998336843307.826456471794235.808824889
#Sta/Elev= 30
9674.959315.55749679.057316.15279689.936 315.8589700.815316.32379722.572314.3328
 9744.33313.01099776.967307.92139820.482 299.596 9842.24297.61859853.119295.3749
9868.315294.2363 9928.98286.40239950.574285.50679972.169283.56289982.966279.9568
9999.906 270.40310004.59268.226610015.47271.729910023.88273.469710037.65274.7968
10048.87280.458210060.09284.058410071.31 284.59310104.97285.220310138.63284.6645
 10160.7283.688810193.79284.330410258.39 282.99710268.99283.2424   10325281.4176
#Mann= 3 , 0 , 0
9674.959    0.04       09674.959    0.04       0   10325    0.04       0
#XS Ineff= 2 , 0
       0                               0
Bank Sta=9674.959,10325
Exp/Cntr=0.3,0.1

Type RM Length L Ch R = 1 ,19138.48,70.114200,70.114200,70.114200
XS GIS Cut Line= 6
842655.521336046794145.922683899 842899.90496733794235.727180189
842945.451768097794244.998905051 843026.28407817794251.408397746
843086.211689935794260.582702994843296.809344501794314.885031064
#Sta/Elev= 30
9666.947310.08899677.094311.84439709.212312.91789719.918  312.26 9741.33310.0048
9773.448304.18429784.154303.70529816.272297.91759826.978296.92219858.978292.2321
9893.298 288.2239911.658285.35599922.194282.16659932.562276.73759963.177273.1981
9983.429272.22329993.468270.8392 10003.5264.906910023.56269.693810033.59271.1342
10043.61274.764910053.64  279.2310063.75282.241510073.87283.065410114.33283.4166
10134.85282.734810206.81282.682910217.18282.149210289.74281.578810333.08279.9661
#Mann= 3 , 0 , 0
9666.947    0.04       09666.947    0.04       010333.08    0.04       0
#XS Ineff= 2 , 0
       0                               0
Bank Sta=9666.947,10333.08
Exp/Cntr=0.3,0.1

Type RM Length L Ch R = 1 ,19068.37,226.774700,226.774700,226.774700
XS GIS Cut Line= 4
842764.714474261794293.367082059842905.673788339794316.860301092
843008.189653188794317.572216824843246.681421995794392.323368236
#Sta/Elev= 30
9794.813299.87079825.516294.8426 9855.93288.92599866.068287.35959876.206284.9791
9896.482281.6021 9906.62 280.4279916.758278.48789926.896277.35049937.034277.4673
9957.043276.13079967.044275.82449977.044274.36399987.044268.45019997.044264.1193
10007.04267.063410017.04271.550110027.05274.036510037.05275.905610047.37274.8842
10057.85274.984810078.81278.468710098.51 278.45610131.21280.310310141.69281.2604
10165.38281.644510194.09281.142110215.05281.407110256.97280.539210290.17278.8613
#Mann= 3 , 0 , 0
9794.813    0.04       09794.813    0.04       010290.17    0.04       0
#XS Ineff= 2 , 0
       0                               0
Bank Sta=9794.813,10290.17
Exp/Cntr=0.3,0.1

Type RM Length L Ch R = 1 ,18841.59,148.444500,148.444500,148.444500
XS GIS Cut Line= 6
842590.970204241794439.913187094842841.229876631794500.040781723
842882.438933311794496.854962004842950.992444639794465.130427443
842991.425056557794458.848918717843246.580842133794494.689321184
#Sta/Elev= 30
 9663.14308.63619687.955310.93119708.608311.71899729.261309.97879760.241 305.885
9791.221300.23799842.854291.74769883.927287.10819914.356283.00379934.429281.2117
9944.429279.90049954.602277.84859967.407 274.3349986.636 266.4479997.893 260.023
   10001 260.21710009.22261.962410020.51 267.07510031.34273.013510041.96278.1971
10052.27280.071510102.47278.621410152.68279.468410182.89 279.10910193.01279.3947
10213.26279.215710223.39278.765210243.64278.875310253.81278.324410336.87276.9203
#Mann= 3 , 0 , 0
 9663.14    0.04       0 9663.14    0.04       010336.87    0.04       0
#XS Ineff= 2 , 0
       0                               0
Bank Sta=9663.14,10336.87
Exp/Cntr=0.3,0.1

Type RM Length L Ch R = 1 ,18693.15,148.444500,148.444500,148.444500
XS GIS Cut Line= 6
842610.289500879794458.037679973842870.014003534 794533.26448188
842897.182372319794554.402723751842917.001859506 794624.12506642
842953.049792026794663.311817266843183.633677022794731.217637568
#Sta/Elev= 30
 9663.24310.64389688.791310.90169719.812307.58149740.492304.59949792.192295.6329
9823.212290.87439854.264287.1302 9875.24283.71469885.727282.96849896.215280.9659
9917.684 277.8359965.418266.52869969.278266.01349980.213261.8519 9990.61260.1702
10000.77260.749110010.93264.300710021.15267.110810031.78267.5668 10054.6 276.092
10066.14276.759210108.68276.930810152.48276.454410173.66276.948910194.48275.7728
10204.81276.214110215.14275.776910286.97275.835810307.41275.211510336.67275.2361
#Mann= 3 , 0 , 0
 9663.24    0.04       0 9663.24    0.04       010336.67    0.04       0
#XS Ineff= 2 , 0
       0                               0
Bank Sta=9663.24,10336.67
Exp/Cntr=0.3,0.1

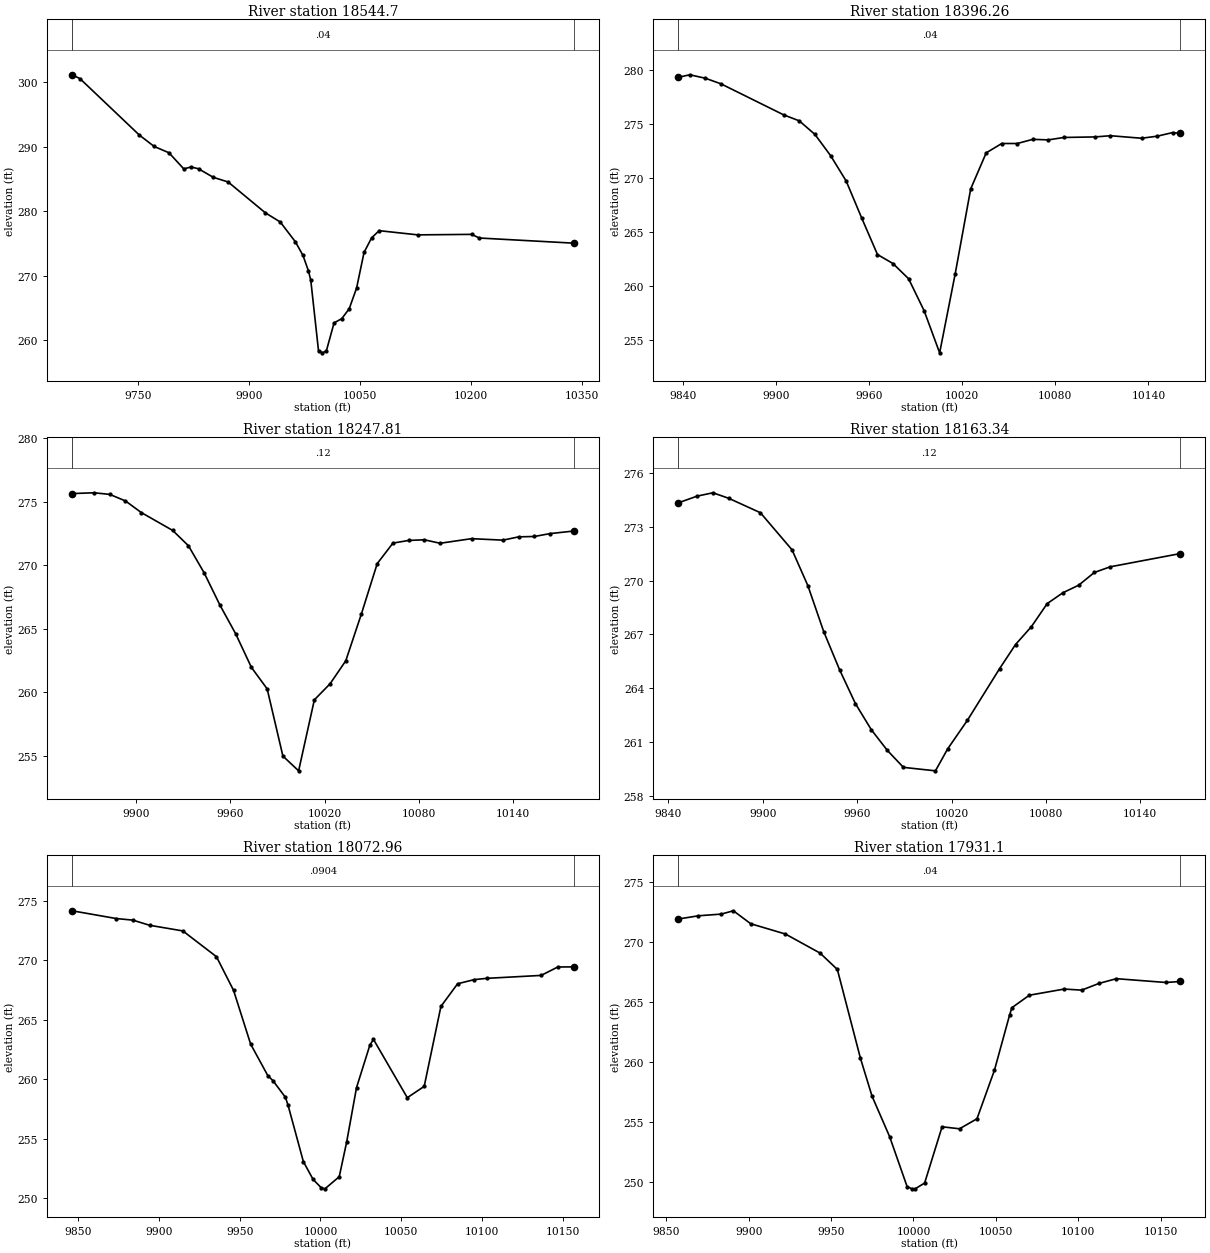
Type RM Length L Ch R = 1 , 18544.7,148.444400,148.444400,148.444400
XS GIS Cut Line= 6
842494.458679858794692.145145272842594.389866935794702.228663766
842696.860182803794703.041589653842771.787003974 794694.84125519
 842879.56754738794670.128780293 843160.13978728794740.436284774
#Sta/Elev= 30
9660.439301.17289671.059300.58249751.481291.81829771.516290.05179791.525289.0752
9811.535 286.5819821.539286.86569831.541 286.5929851.547285.26259871.575284.5436
9921.859279.76659942.124278.33199962.656 275.2569972.922273.13999980.148270.7837
 9983.41269.32459993.935 258.326    9999258.034710004.48258.316510014.95262.6843
 10025.3263.330310035.42264.869310045.42268.079910055.54273.624510065.74275.8681
10075.94 276.98910128.29276.334810201.19276.414710211.45275.8491 10339.5275.0483
#Mann= 3 , 0 , 0
9660.439    0.04       09660.439    0.04       0 10339.5    0.04       0
#XS Ineff= 2 , 0
       0                               0
Bank Sta=9660.439,10339.5
Exp/Cntr=0.3,0.1

Type RM Length L Ch R = 1 ,18396.26,148.444500,148.444500,148.444500
XS GIS Cut Line= 6
842717.726729929794834.814263836842848.093742818 794819.10288845
 842878.50840956794817.803218693842959.476822317 794816.92379868
843007.649159253794818.382978976843039.916694273794820.935547786
#Sta/Elev= 29
9837.238279.28919844.538279.52099854.588279.20029864.666278.68019904.975275.8186
9915.053275.2627 9925.13274.01159935.208272.05419945.285269.69969955.362266.2522
 9965.44262.9071 9975.47262.06959985.479260.67029995.488257.714210005.49253.8213
10015.49261.111310025.49268.972610035.49272.306510045.49273.168410055.49 273.169
 10065.5273.5535 10075.5273.5039 10085.5 273.72810105.51273.776110115.51 273.888
10135.54273.655510145.57273.8434 10155.6274.179610160.54274.1036
#Mann= 3 , 0 , 0
9837.238    0.04       09837.238    0.04       010160.54    0.04       0
#XS Ineff= 2 , 0
       0                               0
Bank Sta=9837.238,10160.54
Exp/Cntr=0.3,0.1

Type RM Length L Ch R = 1 ,18247.81,84.473200,84.473200,84.473200
XS GIS Cut Line= 6
842741.068582413794973.012419933842876.753029609794965.142087002
842886.453539662794964.991742928842888.453432221794964.971012448
843000.298271067 794962.95825273843060.137080653794964.670860335
#Sta/Elev= 29
9859.314 275.6529873.269275.71469883.286 275.5889893.303275.07079903.319274.1614
9923.353 272.748 9933.37271.54299943.387269.40359953.403266.8692 9963.42264.6103
9973.437261.96459983.454260.27399993.471 254.98210003.47253.820210013.48 259.409
10023.48260.674310033.48262.486810043.48 266.19810053.48270.134810063.48271.7517
10073.49271.961810083.49272.013810093.49271.739110113.49 272.101 10133.5271.9854
 10143.5 272.24410153.51 272.27410163.51272.501210178.65272.7037
#Mann= 3 , 0 , 0
9859.314    0.12       09859.314    0.12       010178.65    0.12       0
#XS Ineff= 2 , 0
       0                               0
Bank Sta=9859.314,10178.65
Exp/Cntr=0.3,0.1

Type RM Length L Ch R = 1 ,18163.34,90.384600,90.384600,90.384600
XS GIS Cut Line= 5
842743.232801445795040.103210978842839.409266204795050.589741409
842864.098769426795054.330575213842961.360448688795035.626406133
843059.639163428795036.370941849
#Sta/Elev= 25
9846.412274.34259858.249274.71149868.309 274.8999878.368274.59089898.486273.7877
9918.605271.71939928.664269.72439938.723267.16649948.813265.03859958.927263.1431
9969.048261.68649979.231260.53579989.414 259.59410009.78259.399810017.54260.6229
10030.15262.223810050.51265.0893 10060.7266.441410070.81  267.4410080.81  268.72
10090.81269.327110100.81269.744610110.81270.458110120.82 270.77110165.46271.5111
#Mann= 3 , 0 , 0
9846.412    0.12       09846.412    0.12       010165.46    0.12       0
#XS Ineff= 2 , 0
       0                               0
Bank Sta=9846.412,10165.46
Exp/Cntr=0.3,0.1

Type RM Length L Ch R = 1 ,18072.96,141.861300,141.861300,141.861300
XS GIS Cut Line= 6
842738.473114938795086.882841721842818.236031979795107.015015736
842858.113938957795120.926742792 842899.14805904795140.678257123
842944.012720525795154.802349135843034.636856675795178.805655807
#Sta/Elev= 30
9846.157274.13949873.515273.48839883.829273.35399894.143272.9234 9914.77272.4483
9935.585270.28519946.176267.46079956.767262.94499967.358260.31319970.656259.8678
9978.312258.47959979.973257.79949989.431  253.089995.437251.5941 10000.6 250.874
10002.76250.800410011.63251.816710016.21254.714610022.34 259.296 10030.6262.8594
10032.82263.347110053.79258.450410064.26259.401810074.61266.111310084.95268.0136
 10095.3268.362510103.07268.468810136.68268.714110147.02269.422210156.99269.4309
#Mann= 3 , 0 , 0
9846.157  0.0904       09846.157  0.0904       010156.99  0.0904       0
#XS Ineff= 2 , 0
       0                               0
Bank Sta=9846.157,10156.99
Exp/Cntr=0.3,0.1

Type RM Length L Ch R = 1 , 17931.1,141.861400,141.861400,141.861400
XS GIS Cut Line= 6
842713.630864854795219.989517044842738.021096468795228.890826628
842824.049130887795256.857150301842849.553321987795266.199587986
842953.202711463795302.146471679843001.981244117795317.650608823
#Sta/Elev= 28
9857.415271.92779869.518272.19589883.379272.33779890.717272.61429901.232271.5328
9922.262270.67499943.293269.08399953.808267.71549967.831260.2895 9974.85257.1326
9985.495253.7638 9996.14249.5774    9999249.4017   10001249.395710006.76249.8811
10017.35 254.57710027.93254.410110038.52255.2459 10049.1259.295610058.38263.9434
10059.69264.518410070.27265.563810091.44 266.07810102.02265.987910112.59266.5504
10123.08266.944110153.14266.627210161.89266.7105
#Mann= 3 , 0 , 0
9857.415    0.04       09857.415    0.04       010161.89    0.04       0
#XS Ineff= 2 , 0
       0                               0
Bank Sta=9857.415,10161.89
Exp/Cntr=0.3,0.1