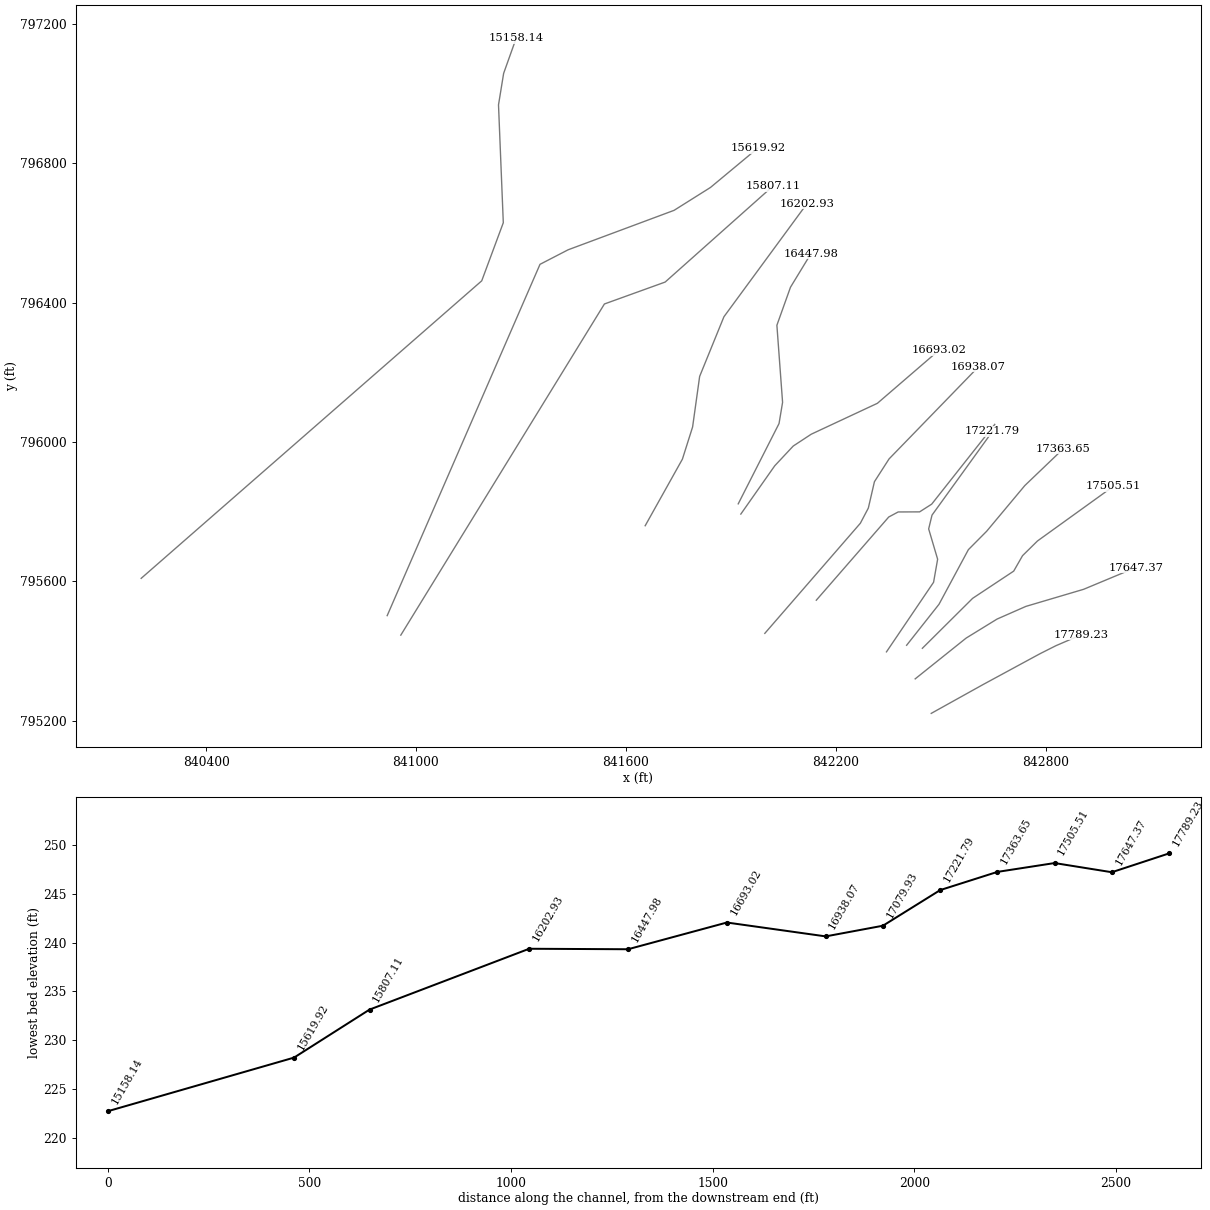
HEC-RAS study 17937_ras.prj: 17937

--- 17937_ras.g01 (geometry) --- (continued)

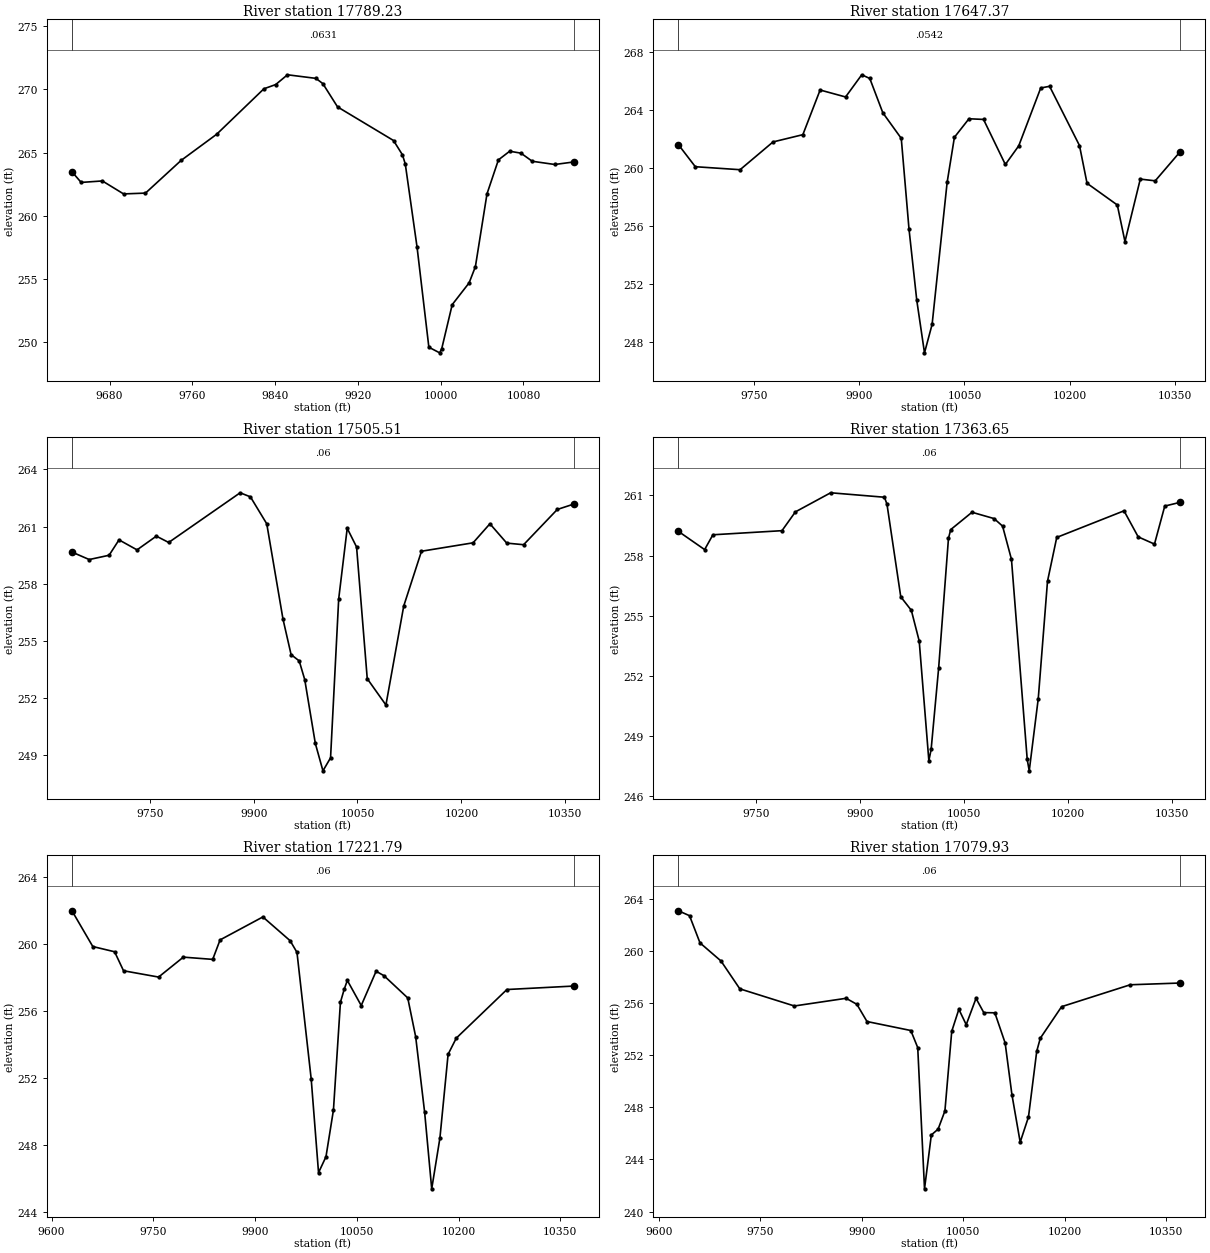
Type RM Length L Ch R = 1 ,17789.23,141.861300,141.861300,141.861300
XS GIS Cut Line= 6
842472.955454051795220.663369805842620.600855082795303.149699897
842777.762638628795388.681610927 842785.96169287795393.047588229
842829.626839727795415.129770562 842901.91756475795446.375328526
#Sta/Elev= 30
9643.657263.47749652.549262.63649673.052262.75329693.556261.72759714.728 261.792
9749.093264.37289783.457 266.4419829.176270.04019840.561270.37399851.946271.1469
9879.411270.86329886.101270.44919900.331268.60719954.411265.9503 9963.09264.8126
9965.796264.08759977.181257.51049988.566 249.607    9999 249.163   10001249.4873
10011.13252.973310027.48254.695510033.54255.974910044.75261.732610055.78264.4176
10066.68 265.10310077.57264.949810088.47264.309310110.26264.054110128.69264.2552
#Mann= 3 , 0 , 0
9643.657  0.0631       09643.657  0.0631       010128.69  0.0631       0
#XS Ineff= 2 , 0
       09888.051                       0
Bank Sta=9643.657,10128.69
Exp/Cntr=0.3,0.1

Type RM Length L Ch R = 1 ,17647.37,141.861300,141.861300,141.861300
XS GIS Cut Line= 6
842427.073817655795319.764010479842572.810540404795436.934523114
842661.198174435795491.539503525842743.623398872795527.923640195
842908.578128606 795576.96683347 843057.25359585795639.264109487
#Sta/Elev= 30
 9642.73261.62549666.782260.10069730.516259.89359777.419261.81389819.885262.3158
9844.466265.40359880.699264.92279903.739266.45679915.189266.20129933.737 263.829
9959.986262.05929971.015255.78529982.043250.86989993.056247.2321 10003.9249.1988
 10025.3259.020210035.65 262.13610056.37263.415510077.09263.370310108.16260.2536
 10127.2261.541710158.54265.543810171.16265.659710213.71261.564110224.47258.9537
10267.55257.454410278.46254.923210300.27259.244310321.52259.124710357.26261.1485
#Mann= 3 , 0 , 0
 9642.73  0.0542       0 9642.73  0.0542       010357.26  0.0542       0
#XS Ineff= 2 , 0
       09915.479        10096.64       0
Bank Sta=9642.73,10357.26
Exp/Cntr=0.3,0.1

Type RM Length L Ch R = 1 ,17505.51,141.861300,141.861300,141.861300
XS GIS Cut Line= 6
 842447.61930975795407.584693078842591.355724076795551.071920549
842708.693076428 795629.19865695 842733.98872658795673.584170041
842776.613357569795715.733292086842994.676170285795873.512964677
#Sta/Elev= 30
9637.586259.66199662.525259.26929691.222 259.494 9705.57260.30229731.593259.7769
9759.482260.49869777.312260.1657 9880.54262.77539895.365262.56089918.957261.1456
9942.392256.14299954.109254.27539965.826253.94679973.815252.9634 9989.11249.6122
10000.12248.1731 10011.1248.856410022.86257.205810035.16260.910410048.68259.9286
10064.09253.012110091.08251.631110116.81 256.83110142.44259.705410216.95260.1474
10241.28261.1472 10265.6260.132110289.93260.048410338.58261.898910362.51262.1831
#Mann= 3 , 0 , 0
9637.586    0.06       09637.586    0.06       010362.51    0.06       0
#XS Ineff= 2 , 0
       09863.823        10040.48       0
Bank Sta=9637.586,10362.51
Exp/Cntr=0.3,0.1

Type RM Length L Ch R = 1 ,17363.65,141.861400,141.861400,141.861400
XS GIS Cut Line= 6
842402.585718474795416.252507182842495.127992279795533.915630802
842579.120516608795690.787567776842631.297460989795743.579422822
842740.502334315795874.921903122842849.978554159795980.143170653
#Sta/Elev= 30
9637.584259.20859675.438258.30049687.407259.03939787.173259.24389806.529260.1813
9857.486261.13399935.191260.91169938.816260.56649958.743 255.9469973.997255.2717
 9985.37253.74279999.321247.772710002.61248.3347 10013.5252.410510027.65258.8628
10030.88 259.29710061.64260.162110093.54259.846810105.79259.472210118.63257.8145
10141.39247.8354 10144.3247.265910157.34250.870410170.69 256.72110184.04258.9077
10281.19260.233510301.68 258.935 10325.2258.574210340.05260.470110362.53260.6601
#Mann= 3 , 0 , 0
9637.584    0.06       09637.584    0.06       010362.53    0.06       0
#XS Ineff= 2 , 0
       09908.984        10065.31       0
Bank Sta=9637.584,10362.53
Exp/Cntr=0.3,0.1

Type RM Length L Ch R = 1 ,17221.79,141.861300,141.861300,141.861300
XS GIS Cut Line= 6
842344.988389403795397.290172815 842479.64572124795597.136609783
842491.219176572795663.313895404842465.612444848795750.385354077
842475.177071927795790.012034712842648.329914995 796030.97647632
#Sta/Elev= 30
9630.054 262.0029660.786259.86689692.917259.55499706.094258.42019757.767258.0437
9794.274259.23359837.553259.09979848.421260.26229911.492261.63389951.662260.2158
9961.775259.51919982.753 251.9559993.566246.365410004.53247.314610015.54 250.101
10025.84256.537410031.39257.312310036.02257.8436 10056.5256.343910078.42  258.39
10090.09258.124710125.07256.797810136.73254.4876   10150249.963510160.41245.3978
10172.49248.429210184.57253.432810196.65254.398310271.28   257.310369.95257.5075
#Mann= 3 , 0 , 0
9630.054    0.06       09630.054    0.06       010369.95    0.06       0
#XS Ineff= 2 , 0
       09941.427        10091.08       0
Bank Sta=9630.054,10369.95
Exp/Cntr=0.3,0.1

Type RM Length L Ch R = 1 ,17079.93,141.861300,141.861300,141.861300
XS GIS Cut Line= 6
842144.395251372795545.663440623842351.460023983795784.581569558
842378.412591431795799.082444824842439.703288792795799.324562423
842474.255056396795821.522980942842654.470452759796050.526444601
#Sta/Elev= 30
9628.996263.07169645.428262.69439660.923 260.6079691.914259.22129719.765 257.084
 9800.38255.76949876.858256.3585 9892.79255.89749907.749254.57719972.525253.8877
9982.755 252.5759992.789241.743210002.85245.874710012.88 246.32410022.93247.7168
10033.03253.825510043.54255.514410054.44254.335310068.91256.352110080.39255.2607
10096.74255.245210111.95252.935610121.96248.9774 10134.2245.324510146.45247.2523
10158.69 252.30410163.95253.295710195.42255.715810296.89 257.39610370.92257.5308
#Mann= 3 , 0 , 0
9628.996    0.06       09628.996    0.06       010370.92    0.06       0
#XS Ineff= 2 , 0
       09892.038        10056.56       0
Bank Sta=9628.996,10370.92
Exp/Cntr=0.3,0.1

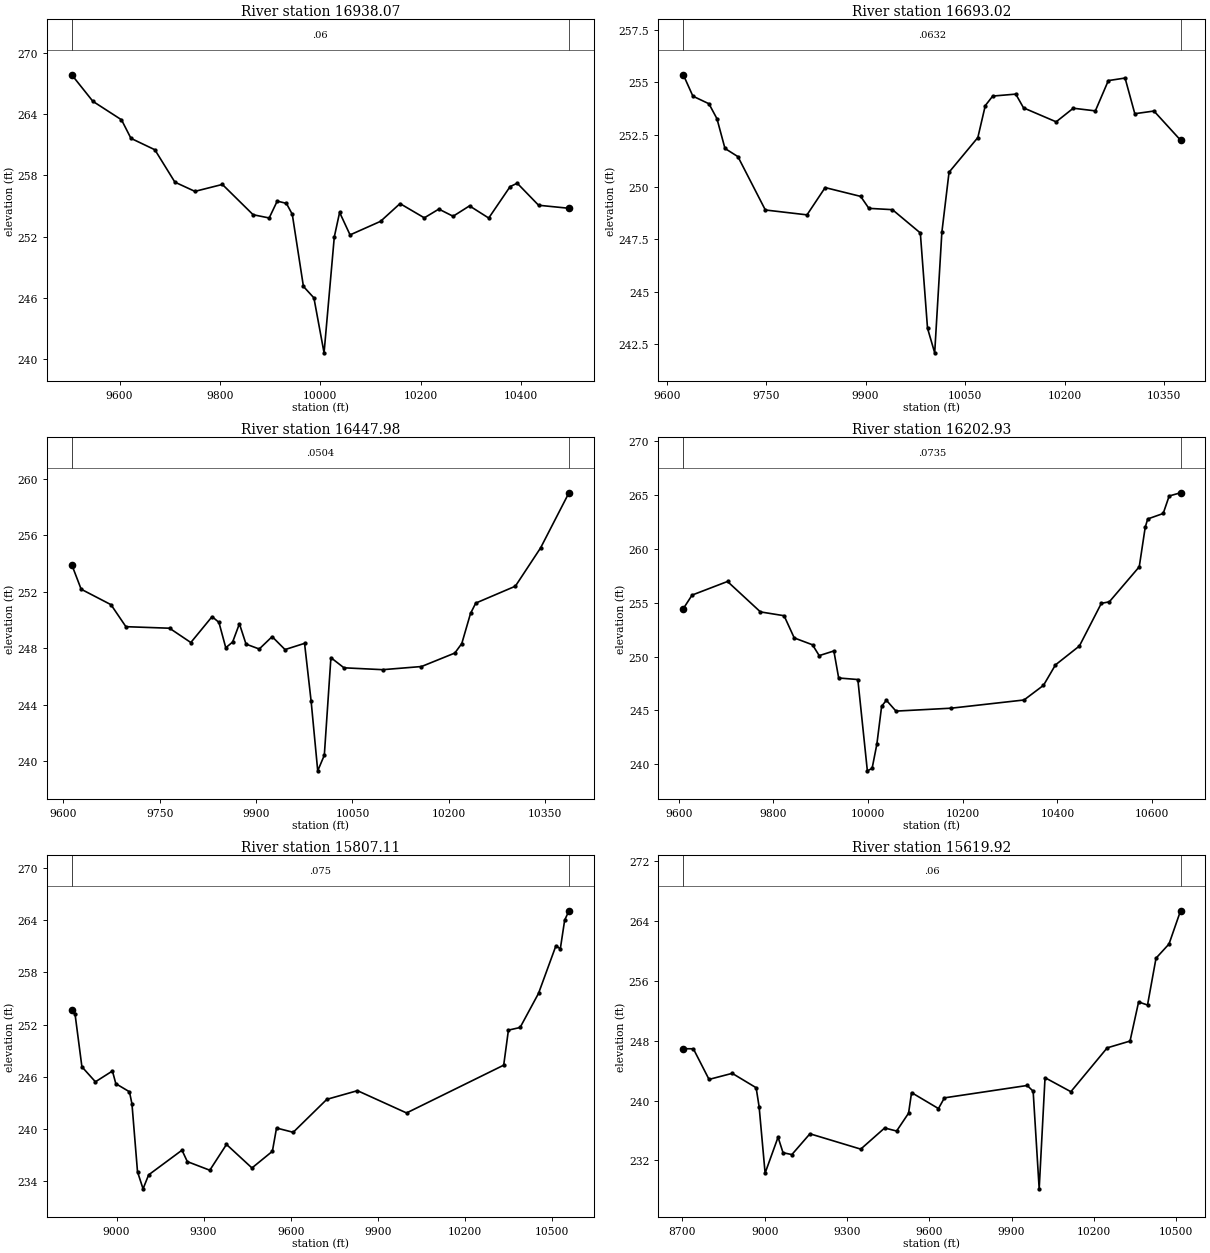
Type RM Length L Ch R = 1 ,16938.07,245.043800,245.043800,245.043800
XS GIS Cut Line= 6
841997.222813312795450.429376297842270.312168487795766.627774333
842293.168852338 795810.32210579842310.560482441 795885.97177097
842352.350775175795951.359379705842607.630416922796215.565390919
#Sta/Elev= 30
9504.739267.83839546.887265.24299603.888 263.4369622.754261.62239670.368260.5056
9710.256257.33929750.144256.43729804.837257.11489866.078254.1532 9898.09253.8364
9914.095 255.4869932.388255.26359944.082 254.1979966.278247.14329987.173246.0226
 10007.4240.647910027.79251.982210038.37254.380110059.18 252.18110119.88253.5054
10158.73255.2411 10207.1253.849210236.05254.704410264.44254.003410297.13255.0187
10335.39253.828310377.97256.901510392.16257.235210434.73255.080110495.23254.7834
#Mann= 3 , 0 , 0
9504.739    0.06       09504.739    0.06       010495.23    0.06       0
#XS Ineff= 2 , 0
       09927.229                       0
Bank Sta=9504.739,10495.23
Exp/Cntr=0.3,0.1

Type RM Length L Ch R = 1 ,16693.02,245.043900,245.043900,245.043900
XS GIS Cut Line= 6
841928.683330823795793.036996032842025.618869306795931.691069673
842078.472487501795988.409336279842130.035407325796022.417407471
842319.064287084796111.128272229842494.274652401796262.782412727
#Sta/Elev= 30
9625.049 255.3569639.518254.33399663.706253.9714  9675.8253.25719687.894251.8358
  9707.4251.44569748.768248.89599811.614248.66329838.982249.96679892.532249.5455
9904.912248.9744 9940.43248.91169982.522247.79899993.367243.248510004.19 242.071
10015.01247.832210025.83250.699210069.27252.3562 10080.5 253.88410091.72254.3389
10126.48254.4324 10138.2253.774110187.37 253.10810213.18253.757810246.51253.6314
10266.08255.077910291.31255.199910306.01253.496110334.89253.6237   10375252.2315
#Mann= 3 , 0 , 0
9625.049  0.0632       09625.049  0.0632       0   10375  0.0632       0
#XS Ineff= 2 , 0
       09930.396                       0
Bank Sta=9625.049,10375
Exp/Cntr=0.3,0.1

Type RM Length L Ch R = 1 ,16447.98,245.043900,245.043900,245.043900
XS GIS Cut Line= 6
841921.214723053795822.361284786842037.881363491796052.973623093
842047.998088127796113.810621401842031.726914393796335.246165868
842070.588875964796444.398779338842129.226525227796541.118031815
#Sta/Elev= 30
9612.955253.91799627.637 252.1749674.105251.0787 9697.29249.52389765.235249.4154
9798.368248.40349831.443250.23279842.099 249.8329852.756248.03599863.412248.4367
9873.996249.72999884.295248.29189904.858247.9446 9924.93248.81889945.009247.9049
9975.407248.34459985.658244.24279995.909239.328910006.17240.432610016.43247.3328
10036.77246.615510097.03246.483210157.44246.705810209.32247.659210220.18248.3329
10233.75250.458310241.89251.191310303.56252.386910342.81255.094310386.99258.9935
#Mann= 3 , 0 , 0
9612.955  0.0504       09612.955  0.0504       010386.99  0.0504       0
#XS Ineff= 2 , 0
       09943.148        10064.09       0
Bank Sta=9612.955,10386.99
Exp/Cntr=0.3,0.1

Type RM Length L Ch R = 1 ,16202.93,395.823900,395.823900,395.823900
XS GIS Cut Line= 6
841655.234010398795759.507499233841761.631771058795950.714116886
841790.798229814 796043.23611775 841810.92142278796188.318150967
841880.315101296796359.595962822842117.435012788   796684.001424
#Sta/Elev= 30
9609.822254.45569628.329255.71549703.192256.9811 9772.74254.1532 9822.74253.7979
9844.182251.7331 9882.79251.09579896.904250.08879927.898250.52159938.044248.0098
9978.562247.86639998.646239.378610008.69239.607510018.74241.858410028.79245.3802
10038.85245.939510059.12244.931310175.97245.203210329.61245.965110370.74247.3254
10396.03249.226710446.62250.983210492.98 254.94910509.84255.090210573.07 258.346
10585.72262.0321   10591262.793110623.66263.3021 10636.3264.929210660.33265.2267
#Mann= 3 , 0 , 0
9609.822  0.0735       09609.822  0.0735       010660.33  0.0735       0
#XS Ineff= 2 , 0
       0 9969.08           10141       0
Bank Sta=9609.822,10660.33
Exp/Cntr=0.3,0.1

Type RM Length L Ch R = 1 ,15807.11,187.193700,187.193700,187.193700
XS GIS Cut Line= 4
840956.669756651795445.365123436841538.690236956796396.332323477
 841712.30134812796459.266351253842020.461070299796734.873990133
#Sta/Elev= 30
8845.648253.66398856.944253.23718880.762247.14588927.289245.42228985.911246.6631
8997.635245.20549044.532244.27679053.169242.89469072.325235.09139091.429233.1355
9110.638234.73969225.576237.57379243.844236.26319321.357235.27189378.826238.2329
9466.605235.53179536.951237.44489551.233240.11699608.702239.62649724.539243.4098
9830.057244.40459999.207 241.84610333.86247.332310350.11251.354110390.36251.6569
10453.86255.576510513.87261.048810528.87260.680810543.87263.978410558.68265.0548
#Mann= 3 , 0 , 0
8845.648   0.075       08845.648   0.075       010558.68   0.075       0
#XS Ineff= 2 , 0
       09946.866        10070.86       0
Bank Sta=8845.648,10558.68
Exp/Cntr=0.3,0.1

Type RM Length L Ch R = 1 ,15619.92,461.775200,461.775200,461.775200
XS GIS Cut Line= 6
840917.734234422795501.334936619841354.571783572796510.201191649
841434.890431911796551.912624776 841737.86773628796665.243684158
841841.848517835796730.929778472841976.789599687796843.613071799
#Sta/Elev= 30
8703.362246.93738740.047246.92368797.148242.83278881.711243.64388968.888 241.721
8979.785 239.174 9001.58230.31149048.816235.10989066.963233.03729099.149232.7861
9165.038235.5661 9350.29233.51599437.467236.34099481.056235.93369524.645238.3182
9535.542241.07049633.617238.93619655.411240.36829957.228242.02249978.858241.2537
10000.85228.208410022.19243.061610116.39241.189710248.79247.0502 10332.1247.9576
10363.33253.185310395.86252.773210426.86259.034710474.21260.927610516.29265.3688
#Mann= 3 , 0 , 0
8703.362    0.06       08703.362    0.06       010516.29    0.06       0
#XS Ineff= 2 , 0
       09931.288        10044.52       0
Bank Sta=8703.362,10516.29
Exp/Cntr=0.3,0.1

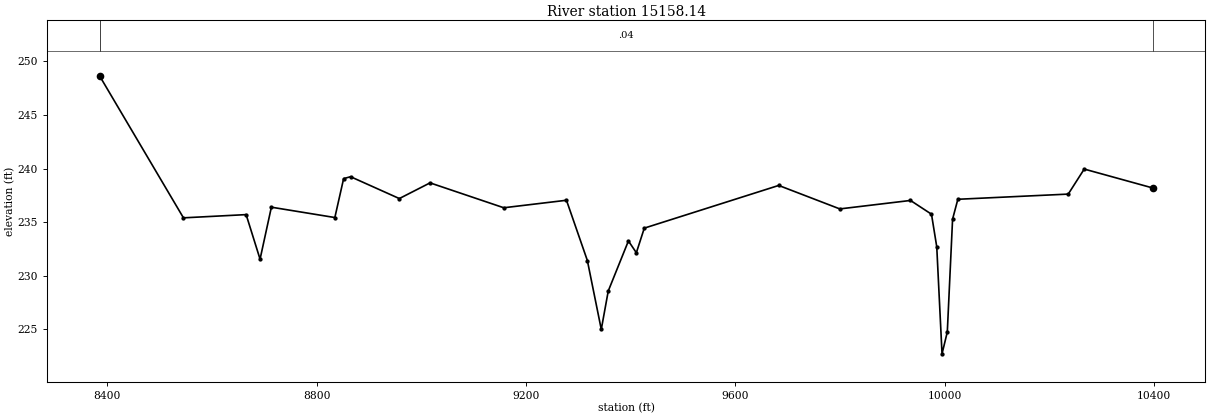
Type RM Length L Ch R = 1 ,15158.14,461.775300,461.775300,461.775300
XS GIS Cut Line= 6
840214.461364359795608.407622725841188.002623945796462.849931881
841249.649285167 796629.68927981841235.943166614796968.051739901
841250.615251869797058.643232942841286.336800009797159.181808397
#Sta/Elev= 30
8385.229248.65418545.609235.39648665.356 235.6988691.966231.53968713.579236.3906
8834.858235.42528851.629 239.0578864.934239.23528958.071237.19659016.776238.6606
 9157.65236.33739277.397237.03769317.313231.41479343.923224.98569357.228228.5679
9395.772233.24059410.932232.13969426.091234.43679682.935  238.429799.647236.2302
  9934.7237.01939974.827235.73599984.883232.6948 9994.96222.705710005.04224.7444
10015.12235.274910025.19 237.129 10236.1237.612510266.64 239.94810397.58238.1836
#Mann= 3 , 0 , 0
8385.229    0.04       08385.229    0.04       010397.58    0.04       0
#XS Ineff= 2 , 0
       09948.849        10038.15       0
Bank Sta=8385.229,10397.58
Exp/Cntr=0.3,0.1