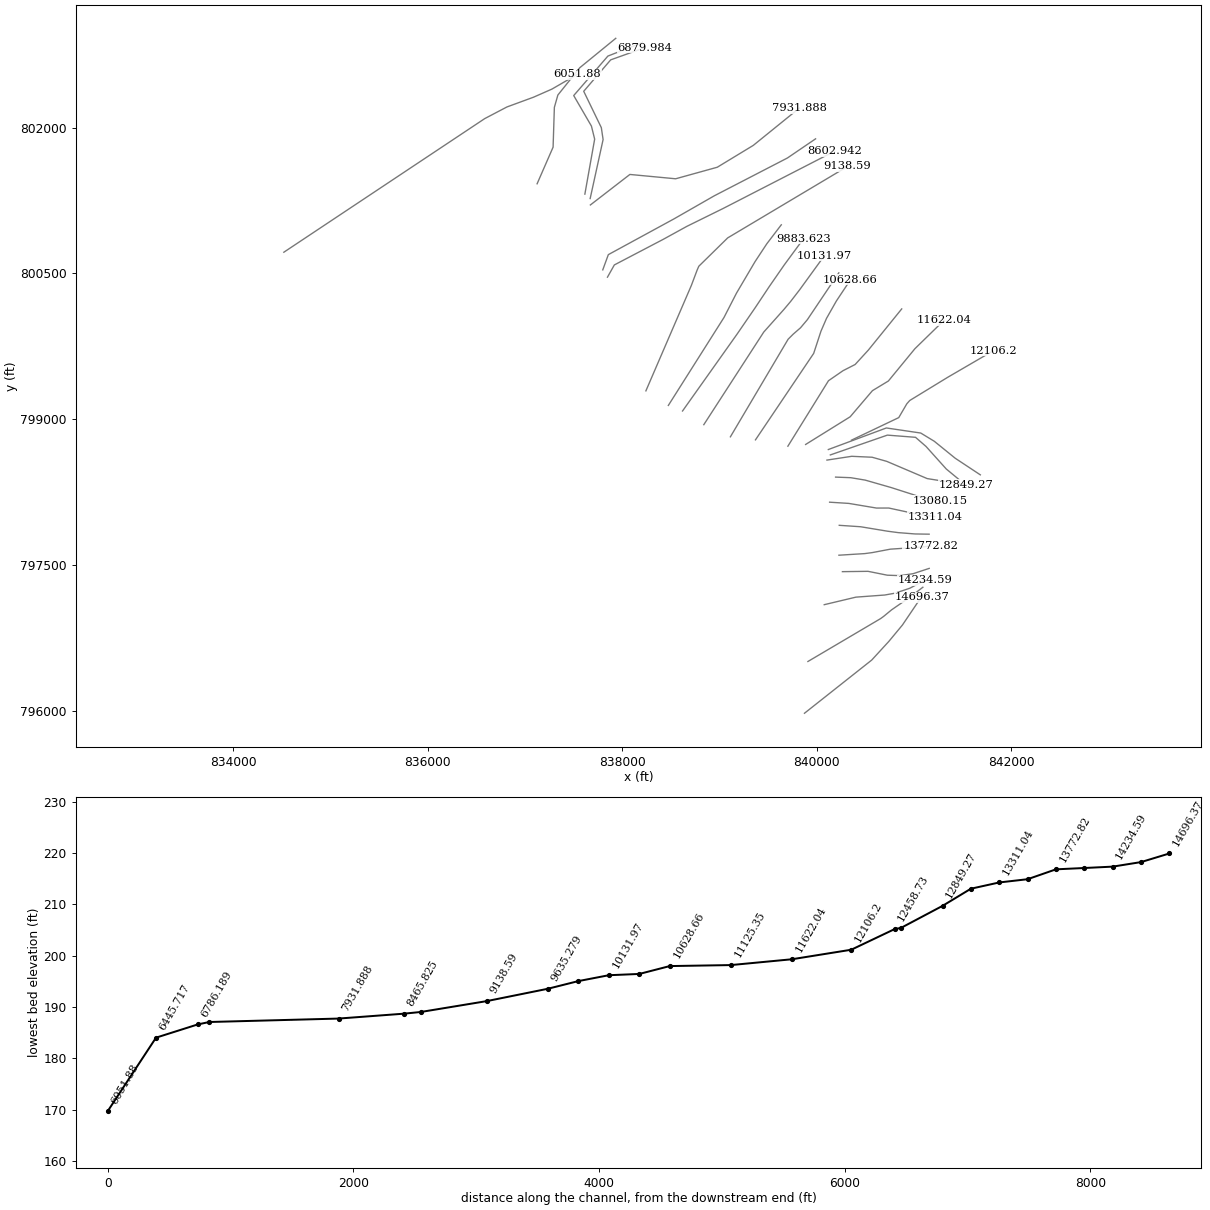
HEC-RAS study 17937_ras.prj: 17937

--- 17937_ras.g01 (geometry) --- (continued)

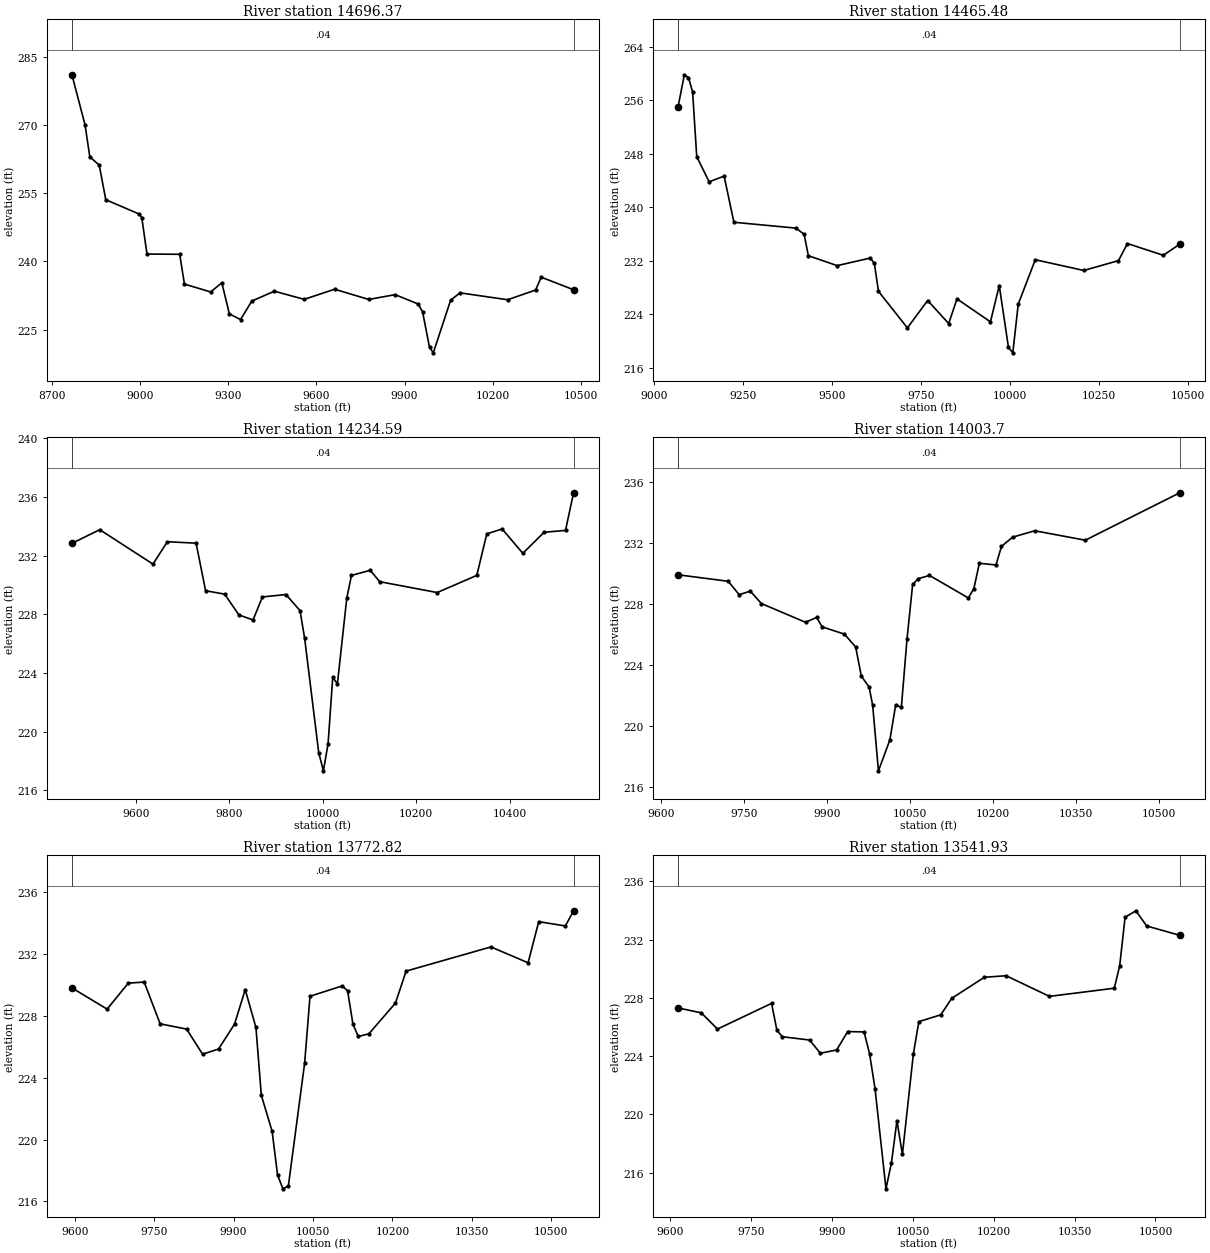
Type RM Length L Ch R = 1 ,14696.37,230.887600,230.887600,230.887600
XS GIS Cut Line= 6
839874.563989162795977.299611405840566.057731748796524.234167784
840742.100379378796716.066091508840881.764595151796884.551628292
841033.971436501797109.818213388841079.033405036797170.580492467
#Sta/Elev= 30
8767.216281.07368811.869270.05818827.988263.04268860.228261.18738882.521253.5851
 8997.27250.40919005.306 249.597 9022.77241.63659134.264241.57919150.384235.0253
9239.518233.29559277.768235.30589303.267228.49419341.517227.21399379.767231.2875
 9456.66233.46049558.265231.66559661.852233.89589778.057 231.6449867.947 232.704
9946.503230.64039961.568228.8864  9985.1221.12279997.965219.899610057.01231.4755
10088.97233.097410251.01231.578710346.58233.718310365.44236.545910475.77233.7816
#Mann= 3 , 0 , 0
8767.216    0.04       08767.216    0.04       010475.77    0.04       0
#XS Ineff= 2 , 0
       09949.576        10077.19       0
Bank Sta=8767.216,10475.77
Exp/Cntr=0.3,0.1

Type RM Length L Ch R = 1 ,14465.48,230.887600,230.887600,230.887600
XS GIS Cut Line= 6
839909.923594862796509.461676762840656.831324905 796950.20223105
840688.539834648796973.235193342840770.441087604797040.693333775
 840952.18445757797166.280649006841091.787771106797272.813824683
#Sta/Elev= 30
9067.391255.06879084.885259.82549096.488259.41579108.091 257.2649119.695247.5769
9154.505243.81429196.604244.66129224.125237.75929398.174236.88279421.381235.9623
9433.192 232.7559514.208231.26889607.034232.40239618.638231.61629630.241227.4246
9711.464221.95049768.359226.05039827.497222.60439850.704226.29469944.744222.8574
9969.464228.28819995.349219.021310007.52218.220510022.87225.523710070.72232.1508
10207.06230.544810304.42232.020310329.58234.574610430.21232.816110476.49234.4791
#Mann= 3 , 0 , 0
9067.391    0.04       09067.391    0.04       010476.49    0.04       0
#XS Ineff= 2 , 0
       09961.432        10074.32       0
Bank Sta=9067.391,10476.49
Exp/Cntr=0.3,0.1

Type RM Length L Ch R = 1 ,14234.59,230.887600,230.887600,230.887600
XS GIS Cut Line= 6
840077.608585529797093.608170649840403.627306452797171.227587746
840700.124580733797192.997874739840807.605267762797212.248928429
840957.214702853797262.652969228841110.041457916797342.507914849
#Sta/Elev= 30
 9463.61 232.8379523.074233.76679636.919231.42099667.682232.94629729.083232.8492
9749.436229.60729790.141229.37579820.525227.96399850.852227.61539871.002229.1846
9921.256229.34959951.292228.25349961.299226.3545 9991.32218.580410001.33217.3365
10011.33219.173710021.33223.706310031.33223.266310051.33229.099910061.35230.6503
10101.48 230.99810121.69230.223910244.69229.484110329.38230.652210350.76233.4816
10383.51233.816310427.81232.157910473.24233.590810519.09233.717310536.34236.2815
#Mann= 3 , 0 , 0
 9463.61    0.04       0 9463.61    0.04       010536.34    0.04       0
#XS Ineff= 2 , 0
       09926.179        10107.38       0
Bank Sta=9463.61,10536.34
Exp/Cntr=0.3,0.1

Type RM Length L Ch R = 1 , 14003.7,230.887600,230.887600,230.887600
XS GIS Cut Line= 6
840264.568008363797433.229281634840527.999575138797436.609645978
840726.096140116797396.837549508840855.622359812797392.405608341
840991.567126185797412.253719315841157.151921004797466.873266622
#Sta/Elev= 30
9630.404229.92539721.014229.50019741.032 228.619 9761.05228.85619781.052 228.042
9861.098226.80949881.131227.13059891.148226.50929931.452226.03419951.777225.1859
9961.996223.27769976.128 222.5649982.549221.35699992.953217.068610013.73219.1031
10024.08221.377410034.44221.241210044.72225.737910054.86229.2903   10065229.6694
10085.27229.885110155.63228.406310165.63 229.01710175.63230.682410205.63230.5692
10215.63231.786110235.68232.392210275.89232.812510367.34232.193510538.27235.3039
#Mann= 3 , 0 , 0
9630.404    0.04       09630.404    0.04       010538.27    0.04       0
#XS Ineff= 2 , 0
       0 9913.88        10088.77       0
Bank Sta=9630.404,10538.27
Exp/Cntr=0.3,0.1

Type RM Length L Ch R = 1 ,13772.82,230.887600,230.887600,230.887600
XS GIS Cut Line= 6
840228.682998359797602.345032796840494.704529673797618.910563216
840572.480414331 797629.36905849840757.614579499 797664.50098671
841068.765305609797685.445032135841170.414034545797696.694602996
#Sta/Elev= 30
9594.648229.81439661.072228.43929701.136230.12049731.184230.19089761.232227.4892
9811.348 227.1489841.434225.52289871.584225.85559901.854227.46949922.034 229.703
9942.244 227.2529952.454222.86469972.875220.52589983.085217.70759993.295216.8106
10003.52216.998610034.19224.925110044.42229.272510105.29229.942310115.41229.6252
10125.53227.465910135.59226.668510155.67226.844710205.88228.832710225.91 230.899
 10386.2232.464510456.39231.439210476.51234.098810526.82233.821510542.33234.8031
#Mann= 3 , 0 , 0
9594.648    0.04       09594.648    0.04       010542.33    0.04       0
#XS Ineff= 2 , 0
       09911.971        10089.31       0
Bank Sta=9594.648,10542.33
Exp/Cntr=0.3,0.1

Type RM Length L Ch R = 1 ,13541.93,230.887700,230.887700,230.887700
XS GIS Cut Line= 6
840232.123849511797909.749769777840451.342783034797895.054925546
840729.438323766797849.076139525840838.167200387797834.617731631
841011.452418327797820.911969051 841156.35392642797818.631904051
#Sta/Elev= 30
9614.874227.30519657.857226.96899687.899225.85759788.133227.6188 9798.18225.7591
9808.227 225.3299858.551 225.1049878.721224.19569908.998224.42429929.289 225.687
9959.724225.6578 9969.87224.16499980.015221.7728 10000.3214.886810010.46216.6653
10020.63219.566810030.79 217.25410051.12224.149810061.29226.365210101.95226.8354
10122.23227.965610182.76229.411610223.11229.518310303.49228.100510423.71228.6601
10433.72 230.20410443.72233.529410463.73233.976910483.74232.935410545.09232.2915
#Mann= 3 , 0 , 0
9614.874    0.04       09614.874    0.04       010545.09    0.04       0
#XS Ineff= 2 , 0
       09947.876        10099.19       0
Bank Sta=9614.874,10545.09
Exp/Cntr=0.3,0.1

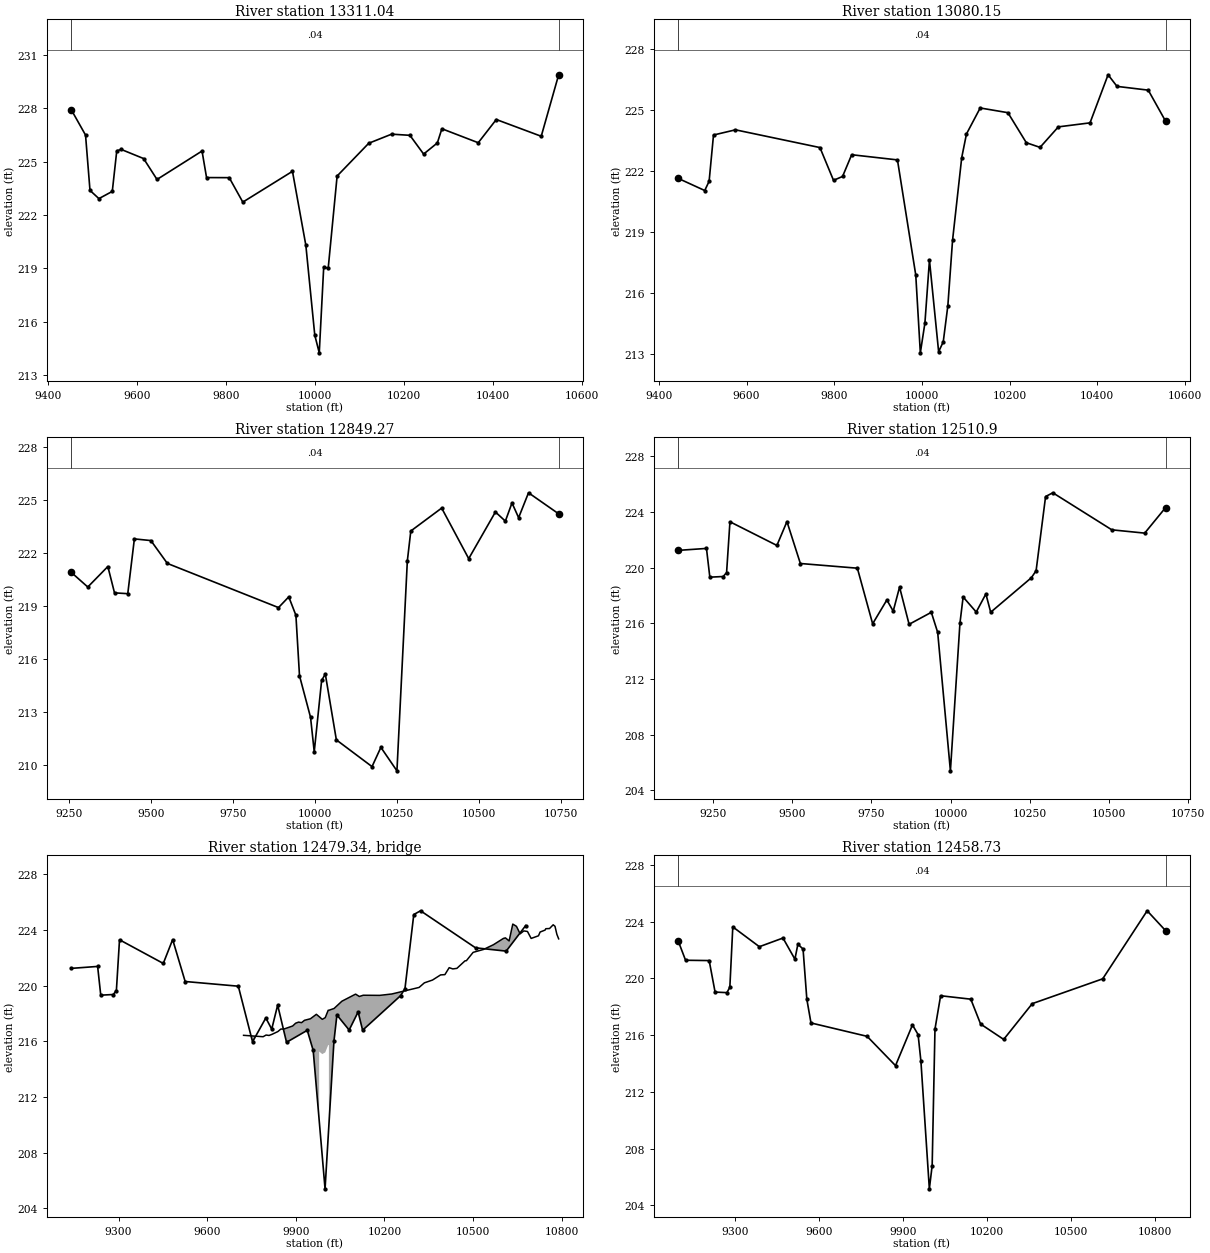
Type RM Length L Ch R = 1 ,13311.04,230.887600,230.887600,230.887600
XS GIS Cut Line= 6
840132.889429042  798147.5125215840330.179476067798135.023607905
840615.184939008798087.182133027 840741.39428656798087.451224349
841031.248082621798025.022764006 841213.88560037798000.368862831
#Sta/Elev= 30
9452.877227.91459485.002226.48919495.006223.37999515.015 222.9189545.054223.3235
9555.093225.60159565.132225.68049615.327 225.1699645.445223.99379746.512225.5916
9756.685224.09999807.553224.09539838.073222.72069949.522 224.4519979.562220.2986
9999.635215.245910009.67214.2547 10019.7219.084310029.72218.999310049.78224.1882
10120.78226.0281 10172.1226.538710213.17226.473910243.96225.420210274.75226.0451
10284.95 226.84310366.57226.057110407.11227.361610507.98226.420110547.11229.8746
#Mann= 3 , 0 , 0
9452.877    0.04       09452.877    0.04       010547.11    0.04       0
#XS Ineff= 2 , 0
       09919.419        10092.76       0
Bank Sta=9452.877,10547.11
Exp/Cntr=0.3,0.1

Type RM Length L Ch R = 1 ,13080.15,230.887600,230.887600,230.887600
XS GIS Cut Line= 6
840194.362225329 798405.46434889840350.038944306798399.433176211
840499.200505483798374.518931585 840765.92264912798298.032853924
841048.676479917798207.406807882841274.115992234798160.540112271
#Sta/Elev= 30
9443.988221.63559504.626221.03559514.626221.49239524.647223.77159574.765224.0276
9767.477223.15339798.455221.53719819.108221.72999839.874222.80019944.308222.5451
9986.082216.86999996.525213.034810006.93214.498610017.32217.604310038.24213.0905
10048.78213.574710059.32215.363510070.03218.586710090.93222.657810101.75 223.823
10133.08225.1049 10196.3224.872510238.32223.391810269.62223.162510311.36224.1736
10383.65224.371110424.84226.741110445.25226.168910516.49225.983410556.04 224.454
#Mann= 3 , 0 , 0
9443.988    0.04       09443.988    0.04       010556.04    0.04       0
#XS Ineff= 2 , 0
       09896.924        10083.44       0
Bank Sta=9443.988,10556.04
Exp/Cntr=0.3,0.1

Type RM Length L Ch R = 1 ,12849.27,338.367100,338.367100,338.367100
XS GIS Cut Line= 6
840105.531914316798580.465691075840360.476678662798619.341673496
840570.110399988798609.752990828840721.006192915798567.201843788
841136.102976821798390.296862952841536.639233755798326.386815726
#Sta/Elev= 30
9257.974220.92859308.413220.09819369.496221.25789389.742219.76799430.129219.7209
9450.239222.82149500.515222.72719550.637221.43369889.041218.93369920.314219.5416
9942.034218.49979952.989215.07699986.629212.72199997.843210.773510020.35 214.808
10031.59215.173310065.21211.4457 10173.8209.933110200.78211.022310249.66209.6936
10281.32221.574910291.87223.267510385.85224.565810468.18221.704910549.48224.3449
10579.77223.827210599.97 224.85710620.14224.020710650.26225.431910742.05224.2408
#Mann= 3 , 0 , 0
9257.974    0.04       09257.974    0.04       010742.05    0.04       0
#XS Ineff= 2 , 0
       0                10089.85       0
Bank Sta=9257.974,10742.05
Exp/Cntr=0.3,0.1

Type RM Length L Ch R = 1 , 12510.9,52.169100,52.169100,52.169100
XS GIS Cut Line= 6
840140.531971604798633.636252195840726.850458384798837.187806427
841016.384278297798814.668509349841124.691373914798720.301930994
841332.726785243798488.674875066841465.820109397798378.589794025
#Sta/Elev= 30
9139.752221.23869229.165 221.3799239.751219.31449282.093219.36179292.678219.6494
9303.264223.29429451.461221.59389483.217223.30699525.559220.29639705.512 219.959
9753.728215.96549798.638217.67649818.685216.87429838.733218.60029868.804215.9275
 9938.98216.78899959.063215.34749999.228205.402210029.35216.011510039.39217.8905
10080.76216.810110111.21 218.10910126.43216.7954 10254.8219.273210269.76219.7785
10299.69225.106310322.57225.376510508.76222.715310612.58222.478310678.53224.3127
#Mann= 3 , 0 , 0
9139.752    0.04       09139.752    0.04       010678.53    0.04       0
#XS Ineff= 2 , 0
       09908.702         10056.5       0
Bank Sta=9139.752,10678.53
Exp/Cntr=0.3,0.1

Type RM Length L Ch R = 3 ,12479.34,,,
BEGIN DESCRIPTION:
END DESCRIPTION:
Bridge Culvert--1,0,-1,-1, 0
Deck Dist Width WeirC Skew NumUp NumDn MinLoCord MaxHiCord MaxSubmerge Is_Ogee
15.084550,22.000000,2.6,0, 60, 59, , , 0.95, 0, 0,0,,
 9723.33 9789.50 9799.50 9809.50 9819.50 9839.50 9849.51 9859.51 9889.51 9899.55
 9909.59 9919.63 9929.68 9949.76 9969.81 9979.26 9979.26 9989.82 9999.8210009.82
10012.2610012.2610029.8210056.1710102.6110115.2810128.4710184.1010225.3910317.68
10335.4910363.0210390.4510405.0010419.5610431.8310445.6010473.1210477.7710500.65
10535.9910569.4710603.1210610.0210622.4510634.8910647.3210659.7610672.1910684.63
10697.0610721.9310727.4110744.2310746.8010759.2410771.6710777.8810784.1110790.24
  216.43  216.33  216.45  216.42  216.50  216.70  216.88  216.88  217.10  217.30
  217.38  217.34  217.51  217.62  217.94  217.77  217.77  217.58  217.70  218.23
  218.23  218.23  218.36  218.88  219.39  219.22  219.31  219.30  219.40  219.87
  220.20  220.40  220.77  220.79  221.29  221.20  221.24  221.78  221.79  222.39
  222.60  222.94  223.39  223.43  223.21  224.42  224.26  223.72  223.93  223.89
  223.39  223.58  223.85  223.99  224.09  224.10  224.37  224.26  223.69  223.36
 -783.57 -783.67 -783.55 -783.58 -783.50 -783.30 -783.12 -783.12 -782.90 -782.70
 -782.62 -782.66 -782.49 -782.38 -782.06 -782.23  215.27  215.08  215.20  215.73
  215.73 -781.77 -781.64 -781.12 -780.61 -780.78 -780.69 -780.70 -780.60 -780.13
 -779.80 -779.60 -779.23 -779.21 -778.71 -778.80 -778.76 -778.22 -778.21 -777.61
 -777.40 -777.06 -776.61 -776.57 -776.79 -775.58 -775.74 -776.28 -776.07 -776.11
 -776.61 -776.42 -776.15 -776.01 -775.91 -775.90 -775.63 -775.74 -776.31 -776.64
 9723.33 9789.50 9799.50 9809.50 9819.50 9839.50 9849.51 9859.51 9889.51 9899.55
 9909.59 9919.63 9929.68 9949.76 9971.18 9971.18 9989.82 9999.8210004.1810004.18
10009.8210029.8210056.1710102.6110115.2810128.4710184.1010225.3910317.6810335.49
10363.0210390.4510405.0010419.5610431.8310445.6010473.1210477.7710500.6510535.99
10569.4710603.1210610.0210622.4510634.8910647.3210659.7610672.1910684.6310697.06
10721.9310727.4110744.2310746.8010759.2410771.6710777.8810784.1110790.24
  216.43  216.33  216.45  216.42  216.50  216.70  216.88  216.88  217.10  217.30
  217.38  217.34  217.51  217.62  217.92  217.92  217.58  217.70  217.93  217.93
  218.23  218.36  218.88  219.39  219.22  219.31  219.30  219.40  219.87  220.20
  220.40  220.77  220.79  221.29  221.20  221.24  221.78  221.79  222.39  222.60
  222.94  223.39  223.43  223.21  224.42  224.26  223.72  223.93  223.89  223.39
  223.58  223.85  223.99  224.09  224.10  224.37  224.26  223.69  223.36
 -783.57 -783.67 -783.55 -783.58 -783.50 -783.30 -783.12 -783.12 -782.90 -782.70
 -782.62 -782.66 -782.49 -782.38 -782.08  215.42  215.08  215.20  215.43 -782.07
 -781.77 -781.64 -781.12 -780.61 -780.78 -780.69 -780.70 -780.60 -780.13 -779.80
 -779.60 -779.23 -779.21 -778.71 -778.80 -778.76 -778.22 -778.21 -777.61 -777.40
 -777.06 -776.61 -776.57 -776.79 -775.58 -775.74 -776.28 -776.07 -776.11 -776.61
 -776.42 -776.15 -776.01 -775.91 -775.90 -775.63 -775.74 -776.31 -776.64
BR Coef=-1 , 0 , 0 ,, 0 ,,,0.8,0,1,0,
WSPro=,,,, 1 ,,,, 0 ,,,, 0 ,,,,-1 ,-1 ,-1 , 0 , 0 , 0 , 0 , 0
BC Design=,, 0 ,, 0 ,,,,,,

Type RM Length L Ch R = 1 ,12458.73,352.534200,352.534200,352.534200
XS GIS Cut Line= 6
 840119.88520658798689.029813051840716.516283065798910.719056413
 841070.00165242798858.634756073841209.406824917798773.919305056
841424.948668599798599.126665637841682.728779465798428.645640954
#Sta/Elev= 30
9095.057222.65039121.586221.28299206.089221.26089227.215219.03869269.466218.9996
9280.029219.37799290.592223.63599385.658222.23839470.161222.84979512.838221.3601
9523.524222.41469542.015222.07269555.582218.52799570.382216.86229771.243215.9187
9872.882213.85289933.527216.72289953.665216.04149963.735214.16979993.943205.1658
10004.01206.808210014.08216.433510034.22218.781510142.26218.538810177.36216.7856
10259.93 215.70210362.15218.223310614.22219.973410773.39224.771510839.29223.3702
#Mann= 3 , 0 , 0
9095.057    0.04       09095.057    0.04       010839.29    0.04       0
#XS Ineff= 2 , 0
       09920.998        10054.66       0
Bank Sta=9095.057,10839.29
Exp/Cntr=0.3,0.1

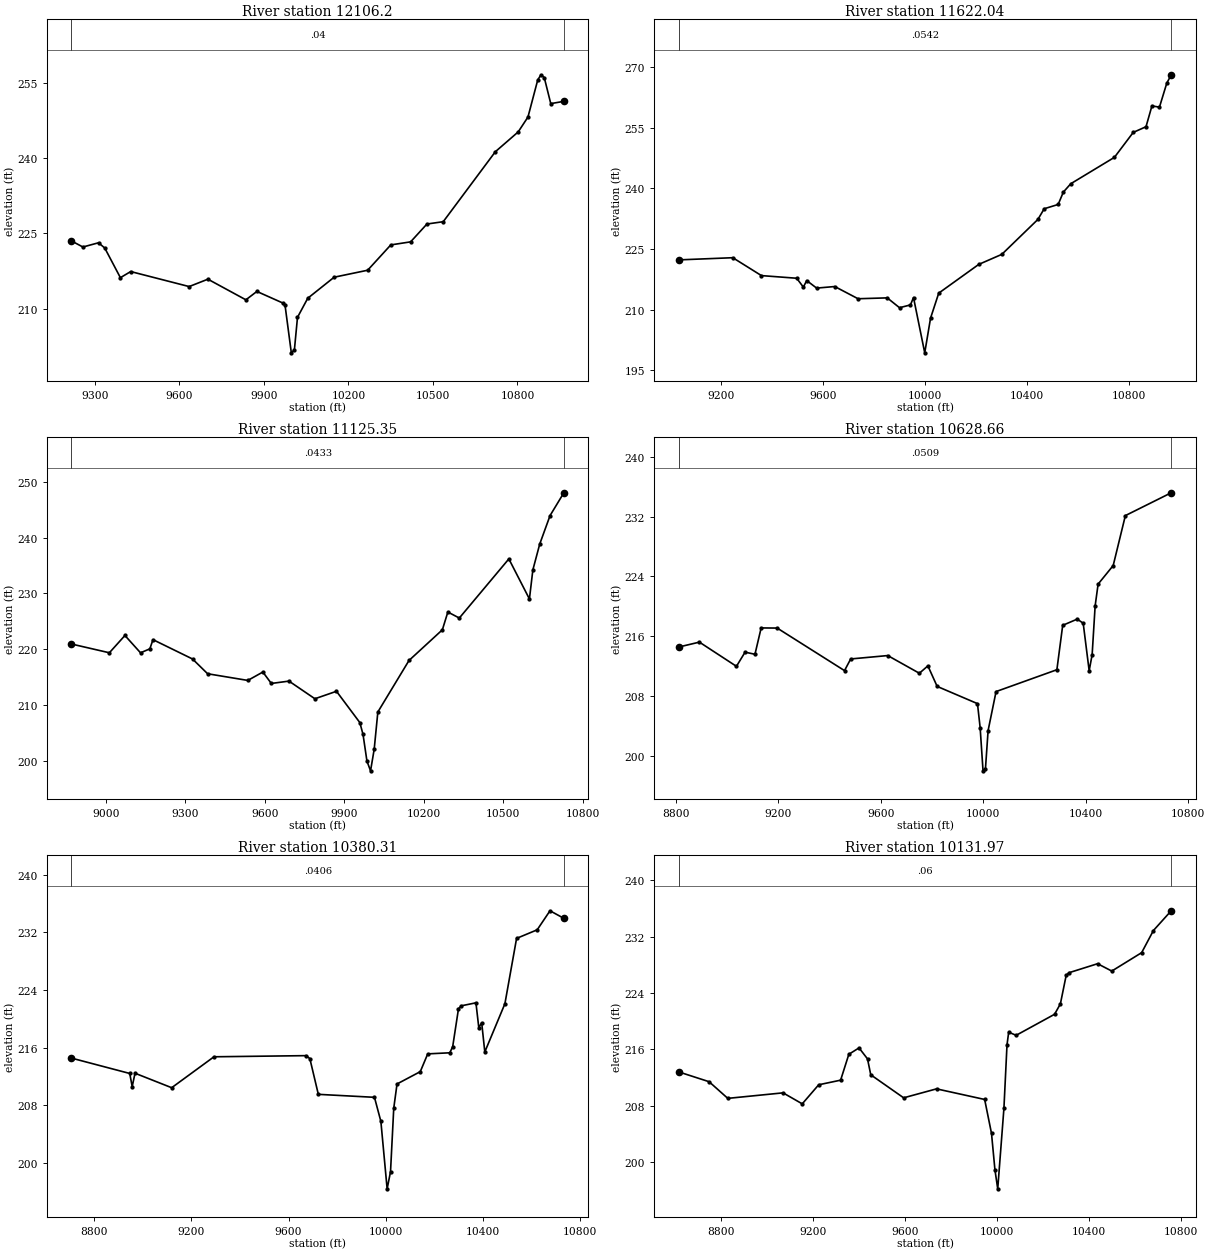
Type RM Length L Ch R = 1 , 12106.2,484.159000,484.159000,484.159000
XS GIS Cut Line= 6
840357.782914246798785.400321017 840843.86867126799017.257725902
840926.880016434  799159.2196362840956.873291173799193.145062331
841348.838034583 799432.68013958841815.118855185799703.984388188
#Sta/Elev= 30
9216.743223.50339257.327222.28889312.749223.1342 9334.94222.08469390.419216.1644
9427.015217.38669634.525214.3894  9701.1215.86169835.984211.74129874.978213.4155
9969.311211.04769974.877210.6934 9997.29 201.15310008.19201.742510019.17208.2443
10055.58212.053810149.32216.2574 10268.3217.652810350.42222.708510420.81223.3195
10478.72226.880310536.57227.343510721.68241.325510802.67245.273410837.38248.2458
10872.08255.657210883.65256.686610895.22 256.13910918.36250.928710964.78251.3781
#Mann= 3 , 0 , 0
9216.743    0.04       09216.743    0.04       010964.78    0.04       0
#XS Ineff= 2 , 0
       0 9820.98        10078.68       0
Bank Sta=9216.743,10964.78
Exp/Cntr=0.3,0.1

Type RM Length L Ch R = 1 ,11622.04,496.689300,496.689300,496.689300
XS GIS Cut Line= 6
839886.448936566798741.146499277 840344.53217038799025.835911536
840573.179582459799294.194258397840737.198154131799393.623892889
841010.167389632799725.802871592841307.896278684800016.233254966
#Sta/Elev= 30
9032.914222.30739244.831222.84659357.332218.41759495.884217.76299522.092215.5625
9535.276217.18879574.213215.32289645.462215.71149736.926212.68899851.584212.9031
 9899.84210.46579942.761211.1613  9954.8212.98689998.894199.295110021.69  207.88
10053.91 214.07610211.13 221.18910301.74223.676510443.32232.317410468.23234.9685
10523.08236.027310543.35239.087310572.66241.162610744.04247.691510817.91253.8642
10868.17 255.27410891.39260.426910920.96260.120410949.63266.037910967.14268.1334
#Mann= 3 , 0 , 0
9032.914  0.0542       09032.914  0.0542       010967.14  0.0542       0
#XS Ineff= 2 , 0
       09793.538                       0
Bank Sta=9032.914,10967.14
Exp/Cntr=0.3,0.1

Type RM Length L Ch R = 1 ,11125.35,496.689400,496.689400,496.689400
XS GIS Cut Line= 6
839703.940945804798723.337190911  840121.4481062799396.635615855
840270.995799392799499.728607148840395.468016177799563.395795524
840530.546141267799710.735158294840874.354571551 800135.04246968
#Sta/Elev= 30
8869.272220.91629012.427219.34699071.259222.44799130.092219.34279165.392220.0491
9177.158221.70149326.692218.22929383.619215.58239535.422214.38589592.349215.8906
9624.287213.84179691.014214.26249788.944211.09739870.458212.43649958.677206.8246
9970.748 204.7039985.564199.90949999.157198.164110012.98202.045810026.74208.7192
10144.51217.968510270.49223.466110291.21226.658510334.53225.5763 10521.7236.1859
10599.41228.9979 10612.4234.2207 10638.4238.859310677.39243.962810729.44248.0507
#Mann= 3 , 0 , 0
8869.272  0.0433       08869.272  0.0433       010729.44  0.0433       0
#XS Ineff= 2 , 0
       09818.557                       0
Bank Sta=8869.272,10729.44
Exp/Cntr=0.3,0.1

Type RM Length L Ch R = 1 ,10628.66,248.344600,248.344600,248.344600
XS GIS Cut Line= 6
839370.607612461798788.441357598839969.268222034799677.710457847
840044.081144124799905.852140769840100.873579115800037.215367854
840202.196957111 800215.78090328840346.622454792800433.383755788
#Sta/Elev= 30
  8811.4214.54168891.636215.19419036.295211.95539069.959 213.8529108.624213.5697
9132.734217.09439195.306217.07549458.216211.38099482.326212.94189626.985213.3967
9750.415211.02889783.698212.01829819.863209.26969977.271206.96429987.661203.7687
    9999197.9715 10008.4198.219310018.76203.356910049.84208.5779 10287.3211.4998
10310.03217.441710366.86218.274910390.04217.719910413.33211.366910424.97213.5174
10436.61220.024410448.25222.957410507.15225.442210554.67232.124610733.64235.1779
#Mann= 3 , 0 , 0
  8811.4  0.0509       0  8811.4  0.0509       010733.64  0.0509       0
#XS Ineff= 2 , 0
       09920.283        10130.25       0
Bank Sta=8811.4,10733.64
Exp/Cntr=0.3,0.1

Type RM Length L Ch R = 1 ,10380.31,248.344700,248.344700,248.344700
XS GIS Cut Line= 6
839112.795112491798819.691357598839706.405129582799823.305681333
839758.152003884799874.987342253839833.975410908799940.932518303
839904.151141465800024.287165642840227.314155638800505.496358946
#Sta/Elev= 30
8705.914214.5684 8945.96212.43898956.065210.61828967.683212.47119118.721 210.462
9292.995214.75229672.749214.91119688.015 214.494 9722.87209.54329954.117209.1312
9980.529205.795510006.33196.437110020.28198.8142 10033.6207.626810047.09210.9825
10142.91212.692310173.58215.156510264.39215.305110276.34216.144310300.25221.4108
 10312.2221.8245 10372.2222.236310383.91218.798110395.87219.469310408.71215.4221
10491.49222.109410539.58231.173410624.51232.363310677.25235.002510734.31233.9577
#Mann= 3 , 0 , 0
8705.914  0.0406       08705.914  0.0406       010734.31  0.0406       0
#XS Ineff= 2 , 0
       09936.933        10066.38       0
Bank Sta=8705.914,10734.31
Exp/Cntr=0.3,0.1

Type RM Length L Ch R = 1 ,10131.97,248.344700,248.344700,248.344700
XS GIS Cut Line= 6
838839.357612491798944.691357598839455.794519305799896.989376277
839661.570316911 800127.73937878839731.569616437800210.811432794
 839824.82190308800331.784874097840080.455628008800684.048025399
#Sta/Elev= 30
8616.746212.79018748.148211.40448829.557 209.0379069.779  209.829153.165208.2586
9224.638210.96749319.936211.62179355.673215.29769400.036 216.2059436.841214.6454
9450.971212.38599593.918209.11459736.865210.3872 9946.05208.88159975.824204.0588
9990.711198.895910002.88196.188410029.77207.602210043.21216.6418 10050.5218.4387
10082.91217.991410250.01 220.98110275.26222.462710300.52226.525110313.14226.8879
10436.88228.160610498.66227.116510628.48229.732210679.56232.873310756.95235.6789
#Mann= 3 , 0 , 0
8616.746    0.06       08616.746    0.06       010756.95    0.06       0
#XS Ineff= 2 , 0
       09911.121        10092.51       0
Bank Sta=8616.746,10756.95
Exp/Cntr=0.3,0.1

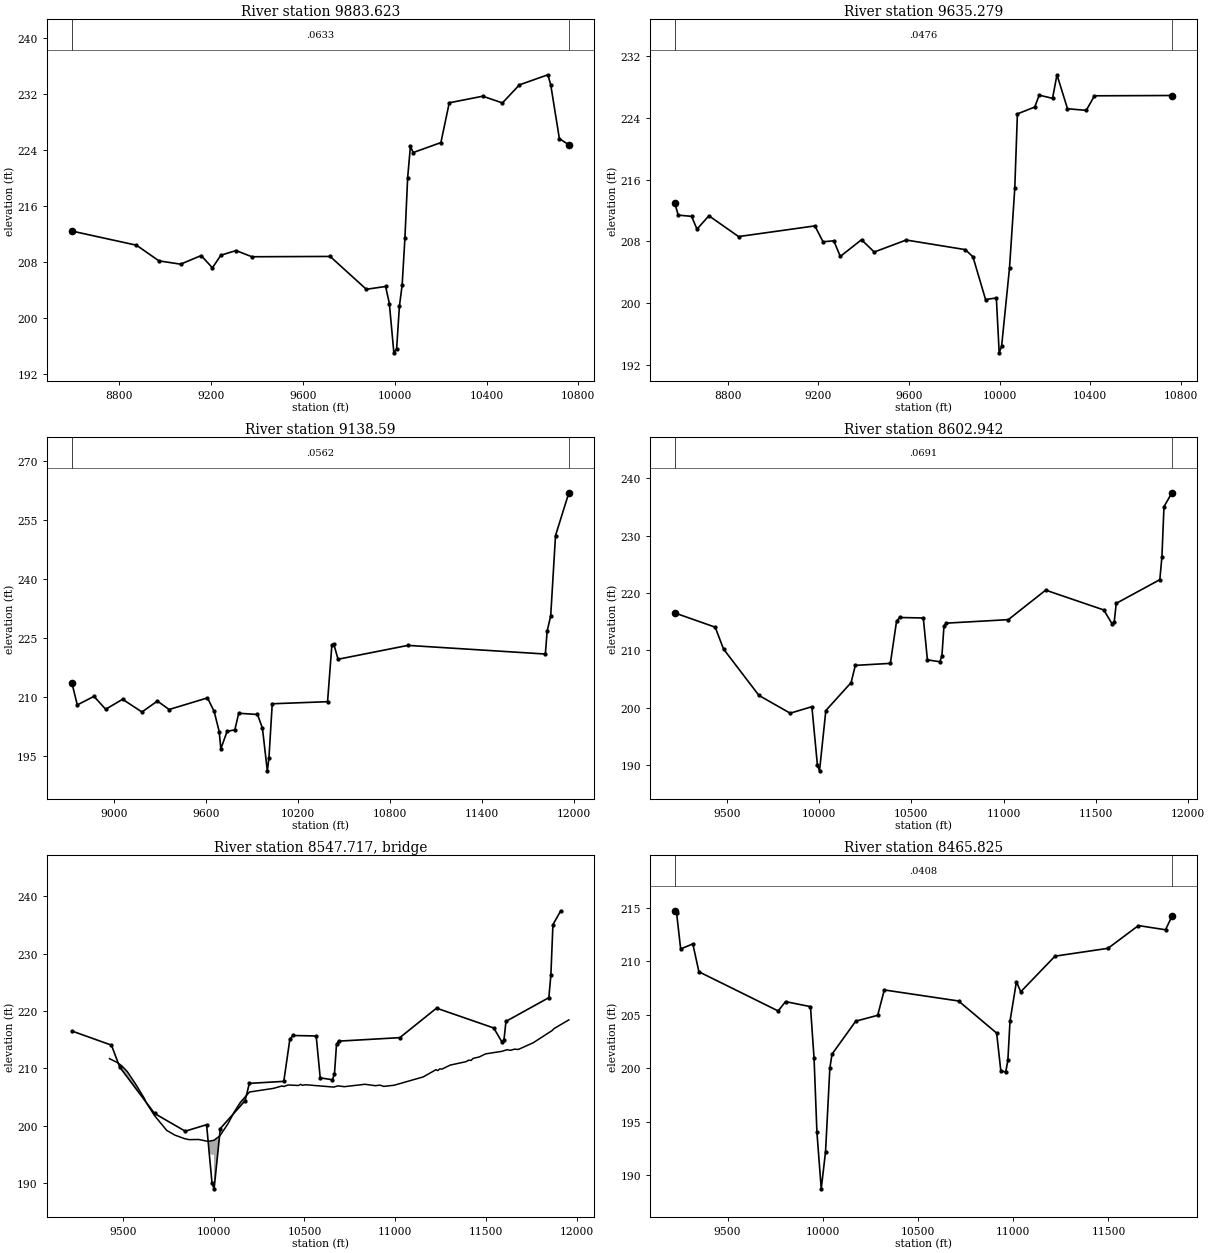
Type RM Length L Ch R = 1 ,9883.623,248.344700,248.344700,248.344700
XS GIS Cut Line= 6
838620.607612491799085.316357598839180.449980259 799874.40684329
839369.407941431800149.693925843 839513.05790022 800365.66630955
 839667.41904211800588.487009168839865.737098426800858.014379323
#Sta/Elev= 30
8592.473212.42698874.144210.40668972.252208.17059066.501207.69749156.204208.9262
9205.257207.17349242.048208.97619308.359209.64129377.461208.75719718.387208.8027
9876.065204.1151 9960.22204.51519976.467202.07819996.201195.042310008.19195.5902
10020.21201.665710032.24204.700610044.26211.373710056.28220.054810068.31224.5047
10080.33223.630510201.12 225.05210237.62230.7336 10383.6231.674110469.34 230.715
10543.28233.291710667.46234.7333   10680233.2897 10717.6225.613210758.99224.7351
#Mann= 3 , 0 , 0
8592.473  0.0633       08592.473  0.0633       010758.99  0.0633       0
#XS Ineff= 2 , 0
       09906.375        10124.53       0
Bank Sta=8592.473,10758.99
Exp/Cntr=0.3,0.1

Type RM Length L Ch R = 1 ,9635.279,496.689300,496.689300,496.689300
XS GIS Cut Line= 6
838474.774279147799142.608024254839046.467660413800046.089131664
839175.857740972800297.884812007839365.505988528800619.817660742
839486.947820236800804.318882939839636.109652085800999.831225134
#Sta/Elev= 30
8567.758212.90278582.422211.39248641.592211.23288665.259209.57378717.794211.3087
8848.706208.61219185.336209.99599221.449207.93629268.784208.06449297.546206.0402
9391.055208.2055 9447.16 206.6129588.298208.16589848.761206.9218 9882.76205.9895
9938.343200.45679985.944200.6564 9998.44193.5494 10009.1194.392510043.97204.5403
10067.22214.862710078.84 224.50710155.37225.395910174.99226.934210233.83226.5236
10253.45229.5754 10299.8225.175210382.59224.964310418.71226.850710760.54226.8903
#Mann= 3 , 0 , 0
8567.758  0.0476       08567.758  0.0476       010760.54  0.0476       0
#XS Ineff= 2 , 0
       09921.886        10157.43       0
Bank Sta=8567.758,10760.54
Exp/Cntr=0.3,0.1

Type RM Length L Ch R = 1 , 9138.59,535.647600,535.647600,535.647600
XS GIS Cut Line= 6
838243.871501356799292.315824062838711.196051038800375.928385859
838770.551941123800533.716039409838788.100275038 800573.86326396
  839085.0173347800865.232490748840316.788168013801599.607490748
#Sta/Elev= 30
8724.115213.58778759.709207.92198868.611210.10898944.843206.82399055.251209.3601
9181.516206.1273 9282.44208.90579358.672  206.769609.148209.71789652.709206.2536
 9685.38201.1592 9696.27196.76159737.078  201.199787.584201.59369812.837205.8054
9935.308205.49339967.406202.04549999.509191.148110010.19194.527610031.51208.2187
10392.47208.752710420.49223.150110432.33223.508210460.88219.555210916.78223.0811
11813.24220.880111824.89226.680811848.17230.620911879.57251.033211966.68261.9271
#Mann= 3 , 0 , 0
8724.115  0.0562       08724.115  0.0562       011966.68  0.0562       0
#XS Ineff= 2 , 0
       09918.269        10162.78       0
Bank Sta=8724.115,11966.68
Exp/Cntr=0.3,0.1

Type RM Length L Ch R = 1 ,8602.942,137.117200,137.117200,137.117200
XS GIS Cut Line= 6
837848.759484172800461.459805444837919.438489079800587.242802486
838419.414207786800848.882638335838666.224255353 800984.46927394
839038.028232664801167.723086089840183.252555907801756.298805535
#Sta/Elev= 30
9219.274216.5179 9437.55214.04799482.696210.24339674.566202.16359843.864199.0697
9961.326200.20299991.273190.019410002.68189.035910036.91199.530210173.83204.4001
10196.65 207.39610386.47207.745310419.91 215.07710436.85215.732410564.84215.6463
10587.14208.351310654.29208.031810665.53209.006410676.78214.202410688.02214.7461
11025.32 215.357 11227.7220.492611542.52217.042611587.49214.619511598.73214.8938
11609.98218.190911846.09  222.3211857.33226.280811868.57235.030511911.58237.4437
#Mann= 3 , 0 , 0
9219.274  0.0691       09219.274  0.0691       011911.58  0.0691       0
#XS Ineff= 2 , 0
       09908.219        10108.82       0
Bank Sta=9219.274,11911.58
Exp/Cntr=0.3,0.1

Type RM Length L Ch R = 3 ,8547.717,,,
BEGIN DESCRIPTION:
END DESCRIPTION:
Bridge Culvert--1,0,-1,-1, 0
Deck Dist Width WeirC Skew NumUp NumDn MinLoCord MaxHiCord MaxSubmerge Is_Ogee
41.058600,55.000000,2.6,0, 60, 60, , , 0.95, 0, 0,0,,
 9426.61 9471.73 9494.21 9524.67 9568.46 9617.86 9629.10 9674.07 9741.51 9786.47
 9839.47 9865.28 9917.44 9966.92 9975.81 9975.8110001.8110001.8110034.6710079.84
10113.7210147.6010197.2410330.0510375.8410387.2810410.1810467.4110478.8610490.30
10505.5810662.0010684.8910719.2310833.7010890.9310916.5910936.7210993.9511154.20
11224.8611234.3311245.7711257.2211303.0111389.2611406.0211417.4711428.9111463.22
11497.5211589.0011615.9511634.7411657.6111677.8111760.2811863.4411874.8811956.37
  211.70  210.99  210.45  209.45  207.38  204.83  204.04  201.81  199.22  198.39
  197.78  197.60  197.63  197.31  197.34  197.34  197.49  197.49  198.27  200.41
  202.43  204.10  205.89  206.53  206.94  206.86  207.12  207.03  207.23  207.06
  207.16  206.75  206.97  206.82  207.24  206.99  207.09  206.87  207.07  208.52
  209.78  209.62  209.92  209.88  210.58  211.17  211.45  211.38  211.74  212.00
  212.53  212.98  213.26  213.15  213.36  213.30  214.47  216.58  216.94  218.45
 -788.30 -789.01 -789.55 -790.55 -792.62 -795.17 -795.96 -798.19 -800.78 -801.61
 -802.22 -802.40 -802.37 -802.69 -802.66  194.84  194.99 -802.51 -801.73 -799.59
 -797.57 -795.90 -794.11 -793.47 -793.06 -793.14 -792.88 -792.97 -792.77 -792.94
 -792.84 -793.25 -793.03 -793.18 -792.76 -793.01 -792.91 -793.13 -792.93 -791.48
 -790.22 -790.38 -790.08 -790.12 -789.42 -788.83 -788.55 -788.62 -788.26 -788.00
 -787.47 -787.02 -786.74 -786.85 -786.64 -786.70 -785.53 -783.42 -783.06 -781.55
 9426.61 9471.73 9494.21 9524.67 9568.46 9617.86 9629.10 9674.07 9741.51 9786.47
 9839.47 9865.28 9917.44 9966.92 9976.36 9976.3610002.3610002.3610034.6710079.84
10113.7210147.6010197.2410330.0510375.8410387.2810410.1810467.4110478.8610490.30
10505.5810662.0010684.8910719.2310833.7010890.9310916.5910936.7210993.9511154.20
11224.8611234.3311245.7711257.2211303.0111389.2611406.0211417.4711428.9111463.22
11497.5211589.0011615.9511634.7411657.6111677.8111760.2811863.4411874.8811956.37
  211.70  210.99  210.45  209.45  207.38  204.83  204.04  201.81  199.22  198.39
  197.78  197.60  197.63  197.31  197.34  197.34  197.50  197.50  198.27  200.41
  202.43  204.10  205.89  206.53  206.94  206.86  207.12  207.03  207.23  207.06
  207.16  206.75  206.97  206.82  207.24  206.99  207.09  206.87  207.07  208.52
  209.78  209.62  209.92  209.88  210.58  211.17  211.45  211.38  211.74  212.00
  212.53  212.98  213.26  213.15  213.36  213.30  214.47  216.58  216.94  218.45
 -788.30 -789.01 -789.55 -790.55 -792.62 -795.17 -795.96 -798.19 -800.78 -801.61
 -802.22 -802.40 -802.37 -802.69 -802.66  194.84  195.00 -802.50 -801.73 -799.59
 -797.57 -795.90 -794.11 -793.47 -793.06 -793.14 -792.88 -792.97 -792.77 -792.94
 -792.84 -793.25 -793.03 -793.18 -792.76 -793.01 -792.91 -793.13 -792.93 -791.48
 -790.22 -790.38 -790.08 -790.12 -789.42 -788.83 -788.55 -788.62 -788.26 -788.00
 -787.47 -787.02 -786.74 -786.85 -786.64 -786.70 -785.53 -783.42 -783.06 -781.55
BR Coef=-1 , 0 , 0 ,, 0 ,,,0.8,0,1,0,
WSPro=,,,, 1 ,,,, 0 ,,,, 0 ,,,,-1 ,-1 ,-1 , 0 , 0 , 0 , 0 , 0
BC Design=,, 0 ,, 0 ,,,,,,

Type RM Length L Ch R = 1 ,8465.825,533.936700,533.936700,533.936700
XS GIS Cut Line= 6
837800.407062024800536.533303007 837857.66650933800693.042458922
838531.960949212801060.296658367838948.254291296801298.632541224
839699.042396098801686.803692043839988.685650229801883.943079665
#Sta/Elev= 30
9223.562214.71029232.578214.49769253.874211.13949317.763211.60989349.708 209.004
9765.811205.34199804.556206.21369935.478205.74449954.344 200.9239969.411193.9898
9992.034 188.70310014.66192.169410037.28199.992110048.59201.299210173.29204.3858
10288.49204.932310323.09207.305610713.09206.272310913.11203.271310934.88199.7698
10960.76 199.61310972.02200.724810983.27204.388211017.05208.078911039.56207.1335
11219.68210.466211497.72211.198711657.67213.326911799.85212.933911833.52 214.186
#Mann= 3 , 0 , 0
9223.562  0.0408       09223.562  0.0408       011833.52  0.0408       0
#XS Ineff= 2 , 0
       09924.807        10101.01       0
Bank Sta=9223.562,11833.52
Exp/Cntr=0.3,0.1

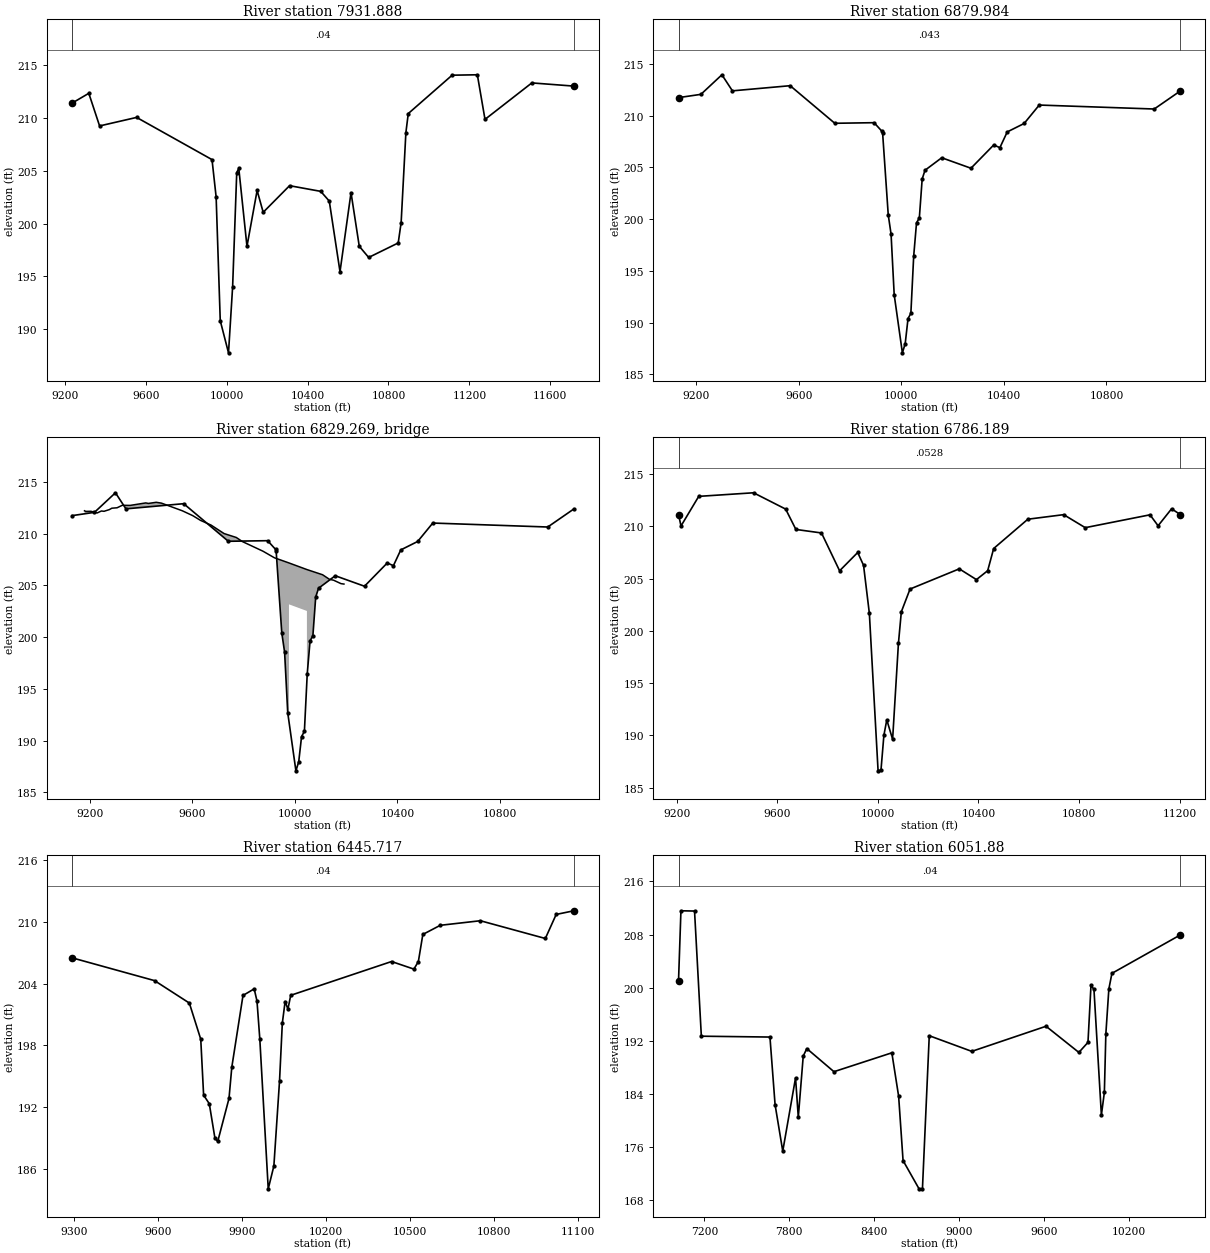
Type RM Length L Ch R = 1 ,7931.888,1051.903900,1051.903900,1051.903900
XS GIS Cut Line= 6
837672.964110136 801203.88342315838079.122675586801517.600182554
838549.681920905801473.090184635838977.903971063801591.805948354
839348.110055109801816.470822422839822.358780252802200.478076816
#Sta/Elev= 30
9235.815211.41829318.547212.34759371.892 209.2559554.905210.06369927.761206.0632
9948.092202.52469968.481 190.79210009.27187.748510029.66194.018410049.99204.8417
10060.11205.226410100.56197.843610150.74203.139910180.76201.069510311.21203.5925
10465.23203.0542 10507.5202.133610560.56  195.44   10615202.933810655.75197.8524
10702.28196.789810848.37198.164110862.81200.097410886.29208.625510898.07210.4287
11114.87 214.065 11239.6214.104511277.43209.876111509.05213.334111716.78213.0314
#Mann= 3 , 0 , 0
9235.815    0.04       09235.815    0.04       011716.78    0.04       0
#XS Ineff= 2 , 0
       09912.785        10064.09       0
Bank Sta=9235.815,11716.78
Exp/Cntr=0.3,0.1

Type RM Length L Ch R = 1 ,6879.984,93.794900,93.794900,93.794900
XS GIS Cut Line= 6
837670.800041556801269.746379644837803.803756565801876.690217048
837785.589765698801998.831096992837604.521268219802372.753615454
 837881.89233467 802695.96165742838230.850667983 802820.96165742
#Sta/Elev= 30
9131.286211.74189218.563212.05899300.461213.9498 9341.41212.39689566.631212.8951
9740.665209.26269893.957209.32029924.935208.47869927.045208.36879949.103 200.419
9960.132198.54959972.348192.694110004.25187.079610015.28187.969310026.31190.3968
10037.34 190.89110048.37196.4269 10059.4  199.6410070.43200.124310081.45203.8769
10092.48204.722310157.72205.931710271.74204.918410360.48207.1658 10384.5206.9063
10413.19208.427610479.08209.243610538.05211.0246 10986.4210.641611088.22212.3863
#Mann= 3 , 0 , 0
9131.286   0.043       09131.286   0.043       011088.22   0.043       0
#XS Ineff= 2 , 0
       09941.675        10128.78       0
Bank Sta=9131.286,11088.22
Exp/Cntr=0.3,0.1

Type RM Length L Ch R = 3 ,6829.269,,,
BEGIN DESCRIPTION:
END DESCRIPTION:
Bridge Culvert--1,0,-1,-1, 0
Deck Dist Width WeirC Skew NumUp NumDn MinLoCord MaxHiCord MaxSubmerge Is_Ogee
19.397450,55.000000,2.6,0, 34, 34, , , 0.95, 0, 0,0,,
 9179.80 9184.68 9205.04 9229.11 9245.74 9255.92 9276.27 9286.45 9306.80 9327.15
 9357.68 9418.74 9428.91 9459.44 9479.80 9561.21 9601.91 9632.44 9673.15 9724.03
 9771.77 9795.13 9876.08 9920.24 9977.20 9977.2010047.2010047.2010108.1710134.85
10151.3510179.9810191.2710191.57
  212.21  212.15  212.16  212.00  212.19  212.16  212.32  212.46  212.50  212.74
  212.73  212.97  212.92  213.03  212.95  212.21  211.74  211.28  210.83  210.01
  209.63  209.24  208.30  207.67  207.17  207.17  206.53  206.53  206.03  205.59
  205.50  205.17  205.13  205.13
 -787.79 -787.85 -787.84 -788.00 -787.81 -787.84 -787.68 -787.54 -787.50 -787.26
 -787.27 -787.03 -787.08 -786.97 -787.05 -787.79 -788.26 -788.72 -789.17 -789.99
 -790.37 -790.76 -791.70 -792.33 -792.83  203.17  202.53 -793.47 -793.97 -794.41
 -794.50 -794.83 -794.87 -794.87
 9179.80 9184.68 9205.04 9229.11 9245.74 9255.92 9276.27 9286.45 9306.80 9327.15
 9357.68 9418.74 9428.91 9459.44 9479.80 9561.21 9601.91 9662.97 9673.15 9724.03
 9771.77 9795.13 9876.08 9920.24 9991.78 9991.7810061.7810061.7810108.1710134.85
10151.3510179.9810191.2710191.57
  212.21  212.15  212.16  212.00  212.19  212.16  212.32  212.46  212.50  212.74
  212.73  212.97  212.92  213.03  212.95  212.21  211.74  210.90  210.83  210.01
  209.63  209.24  208.30  207.67  207.04  207.04  206.40  206.40  206.03  205.59
  205.50  205.17  205.13  205.13
 -787.79 -787.85 -787.84 -788.00 -787.81 -787.84 -787.68 -787.54 -787.50 -787.26
 -787.27 -787.03 -787.08 -786.97 -787.05 -787.79 -788.26 -789.10 -789.17 -789.99
 -790.37 -790.76 -791.70 -792.33 -792.96  203.04  202.40 -793.60 -793.97 -794.41
 -794.50 -794.83 -794.87 -794.87
BR Coef=-1 , 0 , 0 ,, 0 ,,,0.8,0,1,0,
WSPro=,,,, 1 ,,,, 0 ,,,, 0 ,,,,-1 ,-1 ,-1 , 0 , 0 , 0 , 0 , 0
BC Design=,, 0 ,, 0 ,,,,,,

Type RM Length L Ch R = 1 ,6786.189,340.472100,340.472100,340.472100
XS GIS Cut Line= 6
837616.328037858801315.267698586837717.019447118801880.975861967
 837683.80569911  802014.9022654837501.665790409802328.825755104
837853.246501356 802735.02415742838207.413168013802873.044990748
#Sta/Elev= 30
9207.066211.14729216.877210.04959287.439212.88399505.374213.22699633.223211.6645
9673.951209.71659775.769209.38079847.817205.75889919.837207.51169943.073206.2835
9966.195201.683410000.88186.610810012.44186.6851   10024190.015210035.56191.4921
10058.69189.621110081.81 198.80510093.37201.834910128.05204.012310323.94205.9455
10392.17 204.91510436.88205.768610460.73207.892510596.72210.696810739.23211.1326
10825.03209.887211082.61211.117511114.81210.069111168.47211.692911203.26211.1414
#Mann= 3 , 0 , 0
9207.066  0.0528       09207.066  0.0528       011203.26  0.0528       0
#XS Ineff= 2 , 0
       09960.057        10176.43       0
Bank Sta=9207.066,11203.26
Exp/Cntr=0.3,0.1

Type RM Length L Ch R = 1 ,6445.717,393.837600,393.837600,393.837600
XS GIS Cut Line= 6
837125.232458827801421.707851486837289.587042472801798.123610021
837302.707661891802207.705930269837338.721048744802334.367060013
837564.184001327802615.232490733837933.975667983802917.315824091
#Sta/Elev= 30
9291.882  206.529586.879204.2997 9711.27202.11569752.109198.59219762.319193.1517
9782.634192.31449802.795188.96019812.876188.64679853.122192.82799863.133195.8719
9903.176202.85769943.199203.49739953.205202.31489963.259198.62849993.445184.0286
10013.59186.257910033.75194.494210043.79200.154510053.81202.267510063.83201.5277
10073.85202.870910434.51206.159910514.38 205.42110530.36206.161210546.33208.7969
10608.63209.685710752.02210.130810984.44208.402611023.18210.744411086.42211.1003
#Mann= 3 , 0 , 0
9291.882    0.04       09291.882    0.04       011086.42    0.04       0
#XS Ineff= 2 , 0
       09920.616        10165.21       0
Bank Sta=9291.882,11086.42
Exp/Cntr=0.3,0.1

Type RM Length L Ch R = 1 , 6051.88,1049.307100,1049.307100,1049.307100
XS GIS Cut Line= 6
834520.893031577800717.847791915 836586.91856859802092.033592354
836814.965963391802211.599182193837089.356220248802312.360296004
837277.984116344802395.497817522837541.182773632802547.976531522
#Sta/Elev= 30
7017.965201.06437034.902211.57457130.953211.53437178.979192.68747663.298192.5587
7699.435182.38087753.642175.37477843.986186.41817863.343180.47947898.193189.6874
7923.375190.82378115.019187.34238523.694190.1844 8571.72  183.638602.878173.9574
8715.797169.70058739.809169.74158787.835192.75929087.995190.40249612.206194.1848
9844.002190.24239908.216191.76039929.527200.36039950.479199.720210002.91180.8121
10023.92184.219710034.43193.043710055.61199.797910077.22202.152510560.13 207.939
#Mann= 3 , 0 , 0
7017.965    0.04       07017.965    0.04       010560.13    0.04       0
#XS Ineff= 2 , 0
       09944.314        10158.56       0
Bank Sta=7017.965,10560.13
Exp/Cntr=0.3,0.1