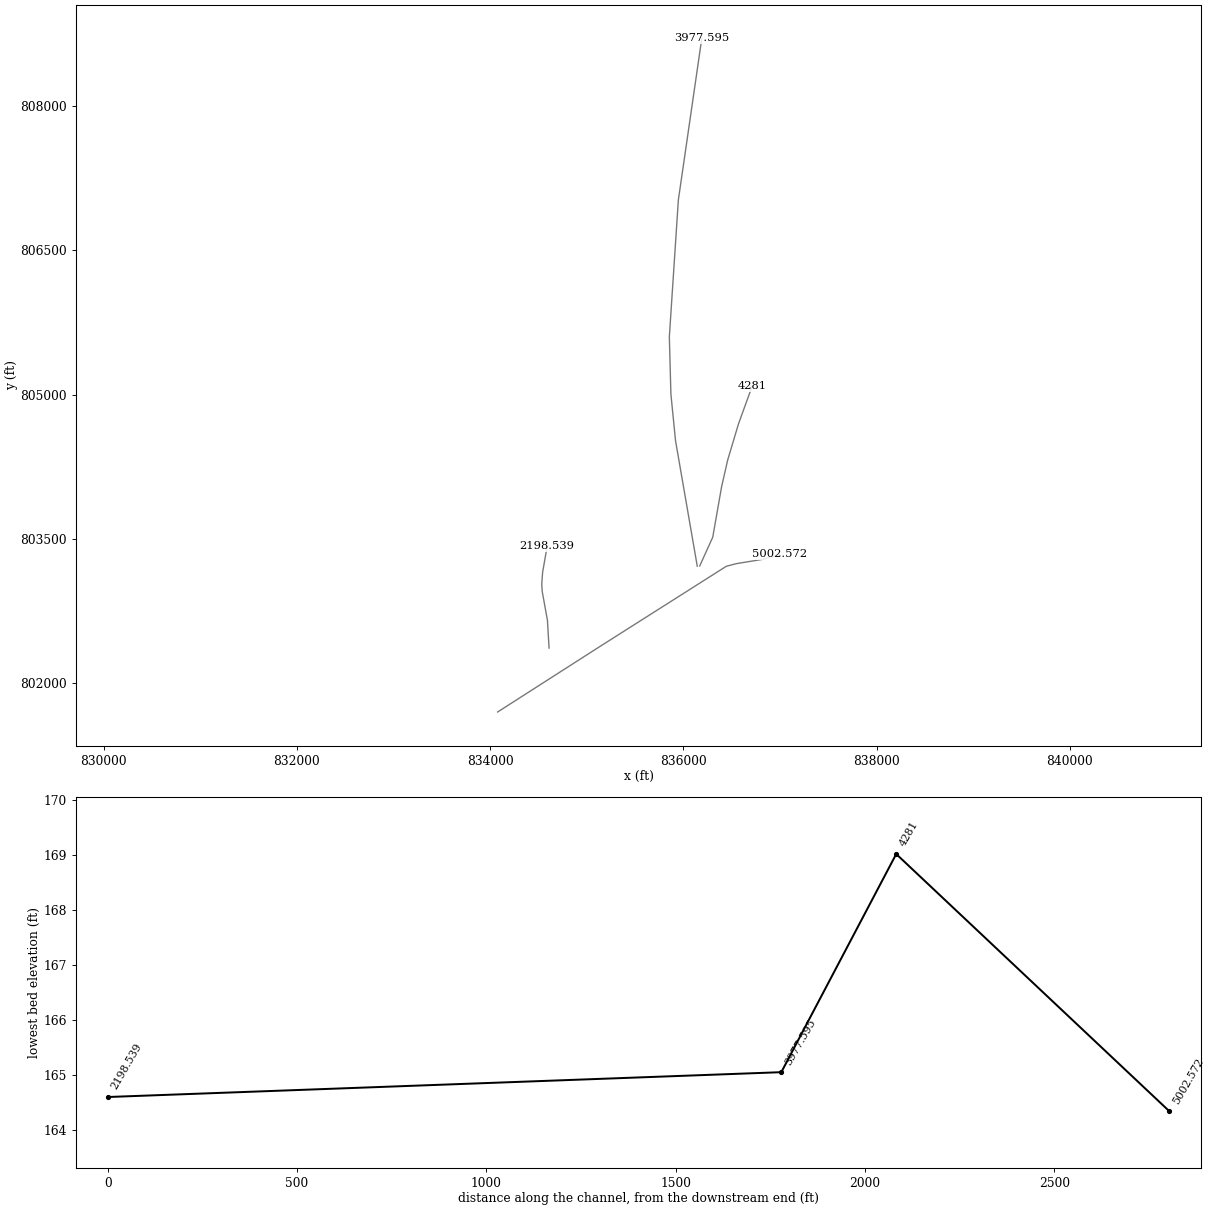
HEC-RAS study 17937_ras.prj: 17937

--- 17937_ras.g01 (geometry) --- (continued)

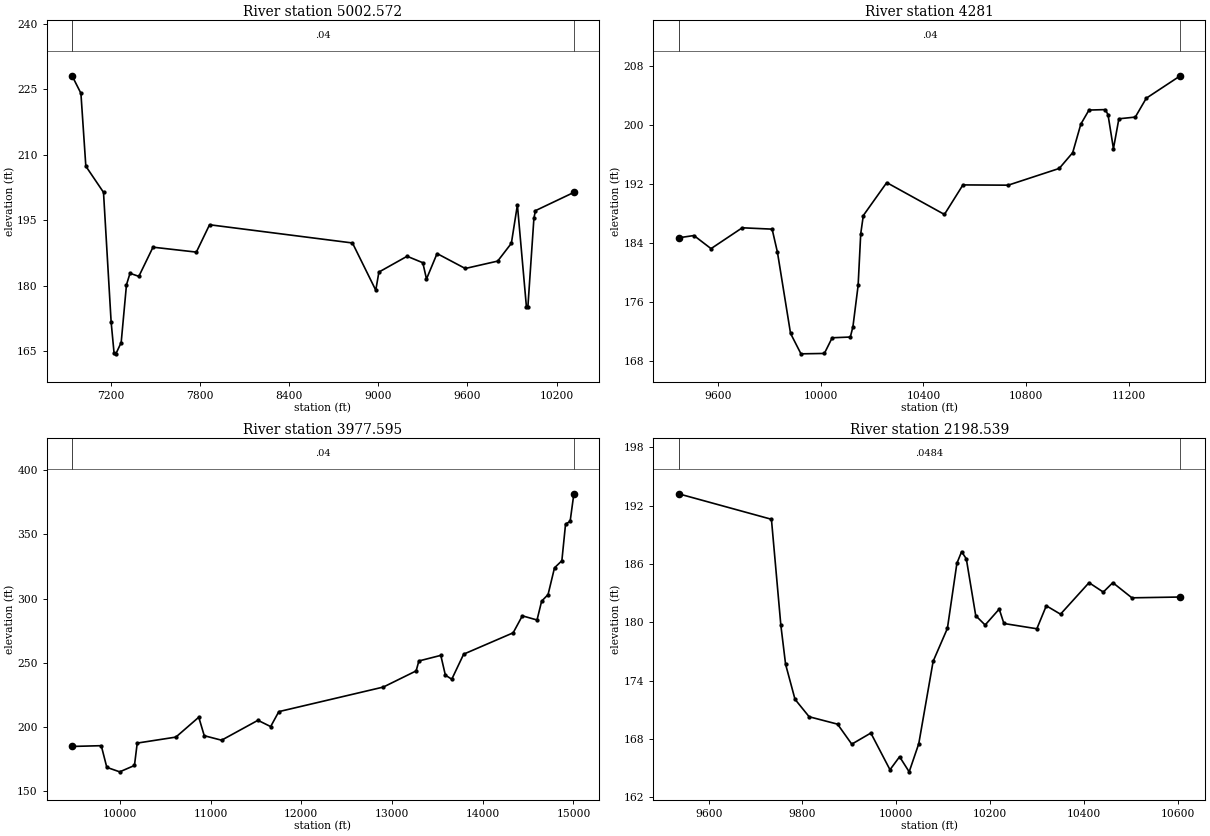
Type RM Length L Ch R = 1 ,5002.572,721.572400,721.572400,721.572400
XS GIS Cut Line= 6
834077.156028658801702.809463665835136.844040424802384.236137852
836444.523134112803217.308458306836548.840899973803244.783162167
836825.893088228803290.330804146 836994.72832151 803340.47087595
#Sta/Elev= 30
6940.798 228.0717000.314224.05687033.348207.35087152.239201.36017203.691171.5831
7223.573 164.4257235.462164.3431 7271.13166.92587306.797180.17517330.575182.7982
7390.021182.10227485.133188.78787776.842187.65787865.584 193.9288826.898189.7522
8983.787178.92489004.751183.0841 9194.46186.70599300.188185.22289324.885181.4945
9396.026187.32679585.736183.90369803.782185.59779895.815189.67359936.348198.4736
9996.962175.155210007.08175.185510047.55195.440510057.67197.1559 10316.2201.3414
#Mann= 3 , 0 , 0
6940.798    0.04       06940.798    0.04       0 10316.2    0.04       0
#XS Ineff= 2 , 0
       09934.126        10143.33       0
Bank Sta=6940.798,10316.2
Exp/Cntr=0.3,0.1

Type RM Length L Ch R = 1 ,    4281,303.404700,303.404700,303.404700
XS GIS Cut Line= 6
836169.406700168803221.113467568836303.916973718803519.142004535
836396.020503649804045.688859422836458.308748162804320.313327998
836570.635661765804697.532278068836712.153781256805089.182653931
#Sta/Elev= 30
9446.409184.74899506.296185.05779572.978183.28259694.543186.10839810.848185.9245
9831.541182.79199882.543 171.7969923.139 169.02210014.27169.0753 10044.6171.1996
10115.36171.300410125.47172.694410145.68178.287310155.79185.2766 10165.9 187.769
10257.13192.234610481.75187.916410553.84 191.92110729.99191.8848 10928.8194.1536
10981.19196.289611012.91200.161211044.65 202.06711108.13202.127711118.71201.4459
11139.87196.833311161.03200.882811224.99201.113711267.71203.671311400.32206.7136
#Mann= 3 , 0 , 0
9446.409    0.04       09446.409    0.04       011400.32    0.04       0
#XS Ineff= 2 , 0
       0                               0
Bank Sta=9446.409,11400.32
Exp/Cntr=0.3,0.1

Type RM Length L Ch R = 1 ,3977.595,1779.056800,1779.056800,1779.056800
XS GIS Cut Line= 6
836143.728517538803218.516797414835918.670561186804523.121013565
835870.815628992  805006.9802483835854.717629131805602.013925869
 835948.09699602807025.302742697836190.844393446808705.429259187
#Sta/Elev= 30
 9473.55184.82729795.398185.42089856.415 168.5469998.678165.055310161.19170.0112
10191.66187.445310617.59192.102810869.95207.585910930.39193.192311121.35189.6811
11522.16205.1842 11662.2200.301311752.21211.935312903.91231.068213265.65243.6524
13295.81 251.39113537.46255.7363 13587.8240.362513658.37237.165913789.49256.6926
14334.92273.309714436.14286.542414598.07283.286714648.69 297.94914719.66 303.093
14790.64323.908414871.75  329.44 14912.3357.875314962.99360.150615003.98381.5722
#Mann= 3 , 0 , 0
 9473.55    0.04       0 9473.55    0.04       015003.98    0.04       0
#XS Ineff= 2 , 0
       0                               0
Bank Sta=9473.55,15003.98
Exp/Cntr=0.3,0.1

Type RM Length L Ch R = 1 ,2198.539,0.000000,0.000000,0.000000
XS GIS Cut Line= 6
834609.494323693802367.166404807 834592.54543733802656.260154592
834538.945409582802953.941979268834533.637980217803031.364688343
834542.932555355803155.970221345834590.132663036803426.570635127
#Sta/Elev= 30
 9535.83193.22679733.879 190.6019753.967179.68529764.017175.68289784.119172.0716
9814.271170.27499874.815169.51229905.136167.45319945.797168.59779986.604164.8192
10007.06166.158110027.51164.603610047.97167.504510078.59175.984610108.99179.3687
10129.24186.072310139.29187.270610149.33186.526610169.43180.674510189.44179.7183
10219.47181.358810229.47179.873710299.68179.331510319.81181.697410350.13180.8332
10410.92184.075110441.33 183.10810461.65 184.07710502.31182.516810605.55182.5995
#Mann= 3 , 0 , 0
 9535.83  0.0484       0 9535.83  0.0484       010605.55  0.0484       0
#XS Ineff= 2 , 0
       09621.569        10331.54       0
Bank Sta=9535.83,10605.55
Exp/Cntr=0.3,0.1